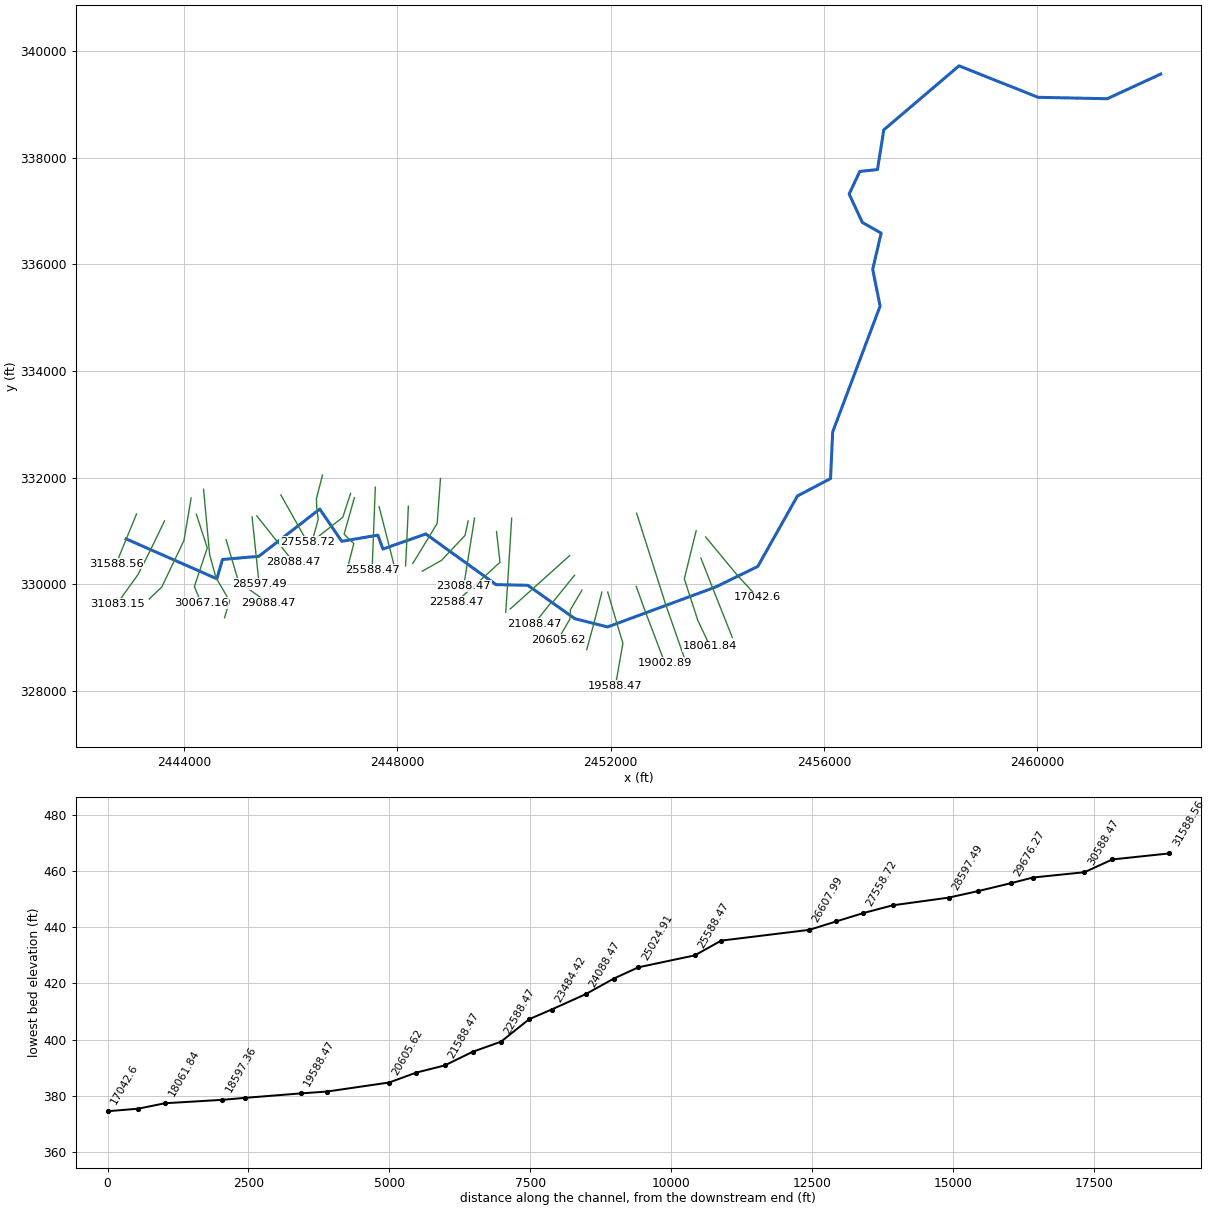
--- RattlesnakeRun.prj (project) ---

Proj Title=Basic Project File
Current Plan=p01
Default Exp/Contr=0.3,0.1
English Units
Geom File=g01
Flow File=f01
Plan File=p01
Y Axis Title=Elevation
X Axis Title(PF)=Main Channel Distance
X Axis Title(XS)=Station
BEGIN DESCRIPTION:
END DESCRIPTION:
DSS File=dss
DSS Export Rating Curves= 0
DSS Export Rating Curve Sorted= 0
DSS Export Volume Flow Curves= 0
DXF OffsetX= 0
DXF OffsetY= 0
DXF ScaleX= 1
DXF ScaleY= 10

--- RattlesnakeRun.p01 (plan) ---

Plan Title=Basic Plan File
Short Identifier=Basic Plan File
Geom File=g01
Flow File=f01
Subcritical Flow
K Sum by GR= 0
Std Step Tol= 0.01
Critical Tol= 0.01
Num of Std Step Trials= 20
Max Error Tol= 0.33
Flow Tol Ratio= 0.001
Split Flow NTrial= 30
Split Flow Tol= 0.02
Split Flow Ratio= 0.02
Log Output Level= 0
Friction Slope Method= 1
Unsteady Friction Slope Method= 2
Calc Critical at every XS
Parabolic Critical Depth
Global Vel Dist= 0 , 0 , 0
Global Log Level= 0
CheckData=True
Encroach Param=-1 ,0,0, 0
Computation Interval=1HOUR
Output Interval=1HOUR
Run HTab= 0
Run UNet= 0
Run PostProcess= 0
UNET Theta= 1
UNET ZTol= 0.02
UNET ZSATol= 0.1
UNET MxIter= 20
UNET MaxInSteps= 20
UNET DtIC= 0
UNET DtMin= 0
UNET MaxCRTS= 20
UNET WFStab= 2
UNET SFStab= 1
UNET WFX= 1
UNET SFX= 1
UNET Convert EG Bridges=-1
UNET Use Existing IB Tables=-1
Instantaneous Interval=1HOUR
DSS File=dss
Write IC File= 0
Write Velocity= 0
Write Detailed= 0

--- RattlesnakeRun.f01 (steady flow) ---

Flow Title=Basic Flow File
Program Version=4.10
Number of Profiles= 1
Profile Names=P1
River Rch & RM=RattlesnakeRun,Reach1          ,31588.56
    1036
River Rch & RM=RattlesnakeRun,Reach1          ,18597.36
    2225
Boundary for River Rch & Prof#=RattlesnakeRun,Reach1          , 1
Up Type= 0
Dn Type= 3
Dn Slope=0.01133
DSS Import GetInterval= 0
DSS Import GetPeak= 0
DSS Import FillOption= 0

--- RattlesnakeRun.g01 (geometry) ---

Geom Title=Generated by CreateGeometryFile written by the GeoFIRM tool.
Program Version=4.10

River Reach=RattlesnakeRun  ,Reach1
Reach XY= 30
2442916.88672319330849.485862434 2444616.9735461330101.742935359
2444722.52910927330464.2428665162445403.77905911330522.923523441
2446546.63602535331409.1874989422446959.12109278 330804.61488919
2447636.56068277330920.0510100132447731.12217344330659.847134098
2448536.75310811330942.1884329322449852.80985919329992.278259277
2450449.59803569 329979.691342192451329.50244386329354.170611605
 2451942.8706397329198.0941521082453965.52669936329944.882356688
2454761.53363752330332.9898481822455505.80445869 331655.38582544
2456125.94331028 331981.913715692456166.04756078332856.392609775
2457055.37058528335215.3337580262456916.68451095335906.553832263
2457075.33576845336584.2572012692456722.03726244336784.344071433
2456475.00593236337316.7573766862456674.22469403337741.236514598
2457005.82179986337775.9585580232457124.74544652338520.750375524
 2458535.3358012339721.2712684422460017.90403028339131.267199099
2461314.23575519339104.3017018592462317.54083519339566.844083861

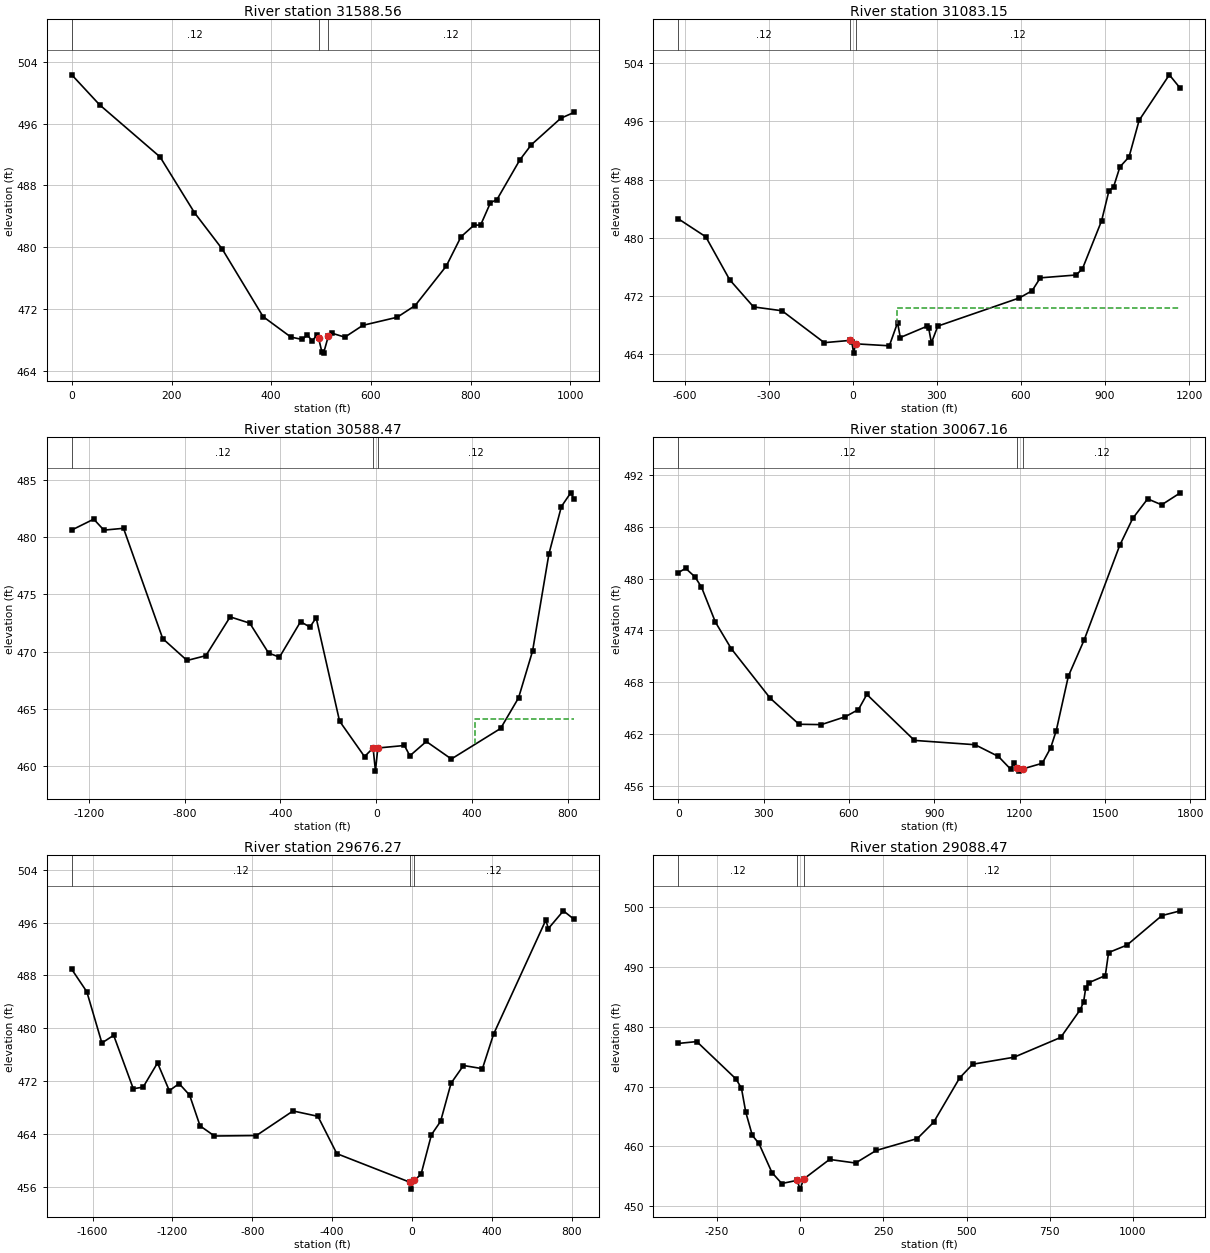
Type RM Length L Ch R = 1 ,31588.56,1014.718,1010.728,1001.757
XS GIS Cut Line= 3
2443110.15175661331316.4691804352442918.77156194330849.163028434
2442728.57049878330384.737120017
#Sta/Elev= 30
       0  502.32   55.74  498.44  177.07  491.68  245.93  484.47  301.67  479.75
  383.65  470.99   439.4  468.34  462.35  468.03  472.19  468.63  482.02  467.85
  491.86   468.6  494.87  468.24   501.7  466.36  504.98  466.26  514.66  468.49
  521.38  468.85  547.62  468.33   583.7  469.86  652.58  470.91  688.67  472.43
  750.99  477.54  780.51  481.33  806.75  482.85  819.87  482.85  839.55  485.74
  852.67  486.16  898.59   491.3  921.55  493.26   980.6  496.69 1006.84  497.44
#Mann= 3 , 0 , 0
       0     .12       0  494.87    .045       0  514.66     .12       0
Bank Sta=494.87,514.66
XS Rating Curve= 0 ,0
Exp/Cntr=0.3,0.1

Type RM Length L Ch R = 1 ,31083.15,493.9902,494.6823,494.9896
XS GIS Cut Line= 4
    2443635.6074    331186.48552   2443365.16109    330625.68677
    2443136.3059     330178.1729   2442748.02059    329637.00633
#Sta/Elev= 30
  -622.6   482.6  -524.3  480.12  -439.1  474.21  -353.9  470.47 -252.32  469.94
 -101.58  465.55   -9.99  465.86   -3.28  465.62    3.26  464.11      10  465.39
  130.55  465.12  159.93   468.3  169.72  466.26  264.37   467.8   270.9  467.55
  280.69  465.53  303.54  467.83  594.06   471.7  639.76  472.69  669.15  474.47
  796.48  474.86  819.34   475.7   887.9  482.33  914.02  486.45  930.35  486.96
   953.2  489.74  985.85  491.12 1021.77  496.15 1129.51  502.41 1168.69  500.55
#Mann= 3 ,-1 , 0
  -622.6     .12       0   -9.99    .045       0      10     .12       0
#XS Ineff= 2 , 0
                           158.8          470.37
Permanent Ineff=
       F       F
Bank Sta=-9.99,10
XS Rating Curve= 0 ,0
Exp/Cntr=0.3,0.1

Type RM Length L Ch R = 1 ,30588.47,875.2925,912.1952,916.5176
XS GIS Cut Line= 5
   2444134.75666    331616.05159   2443999.65523    330818.11814
     2443800.424    330400.34864   2443585.09569    329948.82559
   2443350.03448    329723.69054
#Sta/Elev= 30
-1272.13  480.63-1180.39  481.58 -1137.8  480.62-1055.89  480.78 -892.06  471.14
 -790.49  469.23 -711.86  469.65 -610.29  473.04 -528.37  472.49 -449.81  469.88
 -404.17  469.52 -316.17  472.62 -277.05  472.15 -250.98  472.96  -153.2  463.93
  -48.89  460.83  -13.04  461.58   -3.26  459.56    6.54  461.58   117.7   461.8
  140.59   460.9  209.25  462.15  313.88  460.62  519.77  463.29  594.63  465.96
  653.22  470.05  721.57  478.54  773.65  482.68   812.7  483.88  825.72  483.37
#Mann= 3 , 0 , 0
-1272.13     .12       0  -13.04    .045       0    6.54     .12       0
#XS Ineff= 2 , 0
                          413.45          464.09
Permanent Ineff=
       F       F
Bank Sta=-13.04,6.54
XS Rating Curve= 0 ,0
Exp/Cntr=0.3,0.1

Type RM Length L Ch R = 1 ,30067.16,357.81,390.89,391.52
XS GIS Cut Line= 5
2444231.75515644331313.1607881042444437.59956102 330683.20765169
2444266.52345961330166.4524516022444196.06690761329954.975840434
2444325.07124278329646.494173944
#Sta/Elev= 30
       0  480.68   26.12  481.18   58.76  480.19   81.62  479.01  130.59  474.95
  186.09  471.88   323.2  466.13  424.41  463.11  502.76  463.07  587.64  463.99
  633.35  464.82  662.73  466.57  829.97  461.24 1043.11  460.74 1125.09  459.38
 1167.72  457.92 1180.84  458.62 1191.28  458.03 1197.23  457.68 1211.16  457.94
 1279.19  458.59 1308.69  460.37 1328.36  462.37 1370.97  468.69  1426.7   472.9
 1551.27  483.83 1597.16  486.97 1649.61  489.23 1698.78  488.54 1764.34  489.93
#Mann= 3 , 0 , 0
       0     .12       0 1191.28    .045       0 1211.16     .12       0
Bank Sta=1191.28,1211.16
XS Rating Curve= 0 ,0
Exp/Cntr=0.3,0.1

Type RM Length L Ch R = 1 ,29676.27,584.5273,587.8048,574.9554
XS GIS Cut Line= 5
    2444367.6417    331780.64935    2444482.2248    330553.21874
   2444600.79084    330121.56245   2444856.55443    329687.26575
   2444761.73868    329370.92714
#Sta/Elev= 30
-1703.93  488.92-1628.52  485.53-1553.11  477.78 -1494.1  478.94-1395.74  470.85
-1346.56   471.1-1274.43  474.76-1215.41  470.56-1166.23  471.63-1113.78  469.89
-1061.32  465.23 -989.19   463.7 -779.36  463.77 -595.75  467.49 -471.16  466.68
 -376.41  461.03  -10.99  456.71   -3.88  455.66   10.15  456.97   45.21  457.88
   97.57   463.9  143.39  465.92  195.76  471.69  257.94  474.37  352.85  473.89
  408.49   479.1  670.14  496.36  683.22   495.1  758.42  497.78  810.74  496.52
#Mann= 3 ,-1 , 0
-1703.93     .12       0  -10.99    .045       0   10.15     .12       0
Bank Sta=-10.99,10.15
XS Rating Curve= 0 ,0
Exp/Cntr=0.3,0.1

Type RM Length L Ch R = 1 ,29088.47,512.5273,516.5768,512.5553
XS GIS Cut Line= 4
   2444789.56703    330836.08924   2444893.83093    330484.41048
   2445024.40613    330043.98419   2445581.18323    329648.70513
#Sta/Elev= 30
 -366.81  477.21 -311.13  477.52 -193.23  471.26 -176.85  469.72 -163.75  465.68
  -144.1  461.81 -124.45  460.48  -85.15   455.6  -55.68  453.76  -10.27  454.28
       0  452.82    9.71  454.49   87.97  457.79  166.16  457.19  228.06  459.29
  351.86  461.29  400.73  464.01  478.98  471.44  518.18  473.73  642.33   474.9
  782.82  478.22  841.62  482.87  851.43  484.14  857.96  486.52  867.76  487.39
  916.77  488.57  926.57  492.42  982.11  493.68 1086.66  498.61  1142.2  499.41
#Mann= 3 ,-1 , 0
 -366.81     .12       0  -10.27    .045       0    9.71     .12       0
Bank Sta=-10.27,9.71
XS Rating Curve= 0 ,0
Exp/Cntr=0.3,0.1

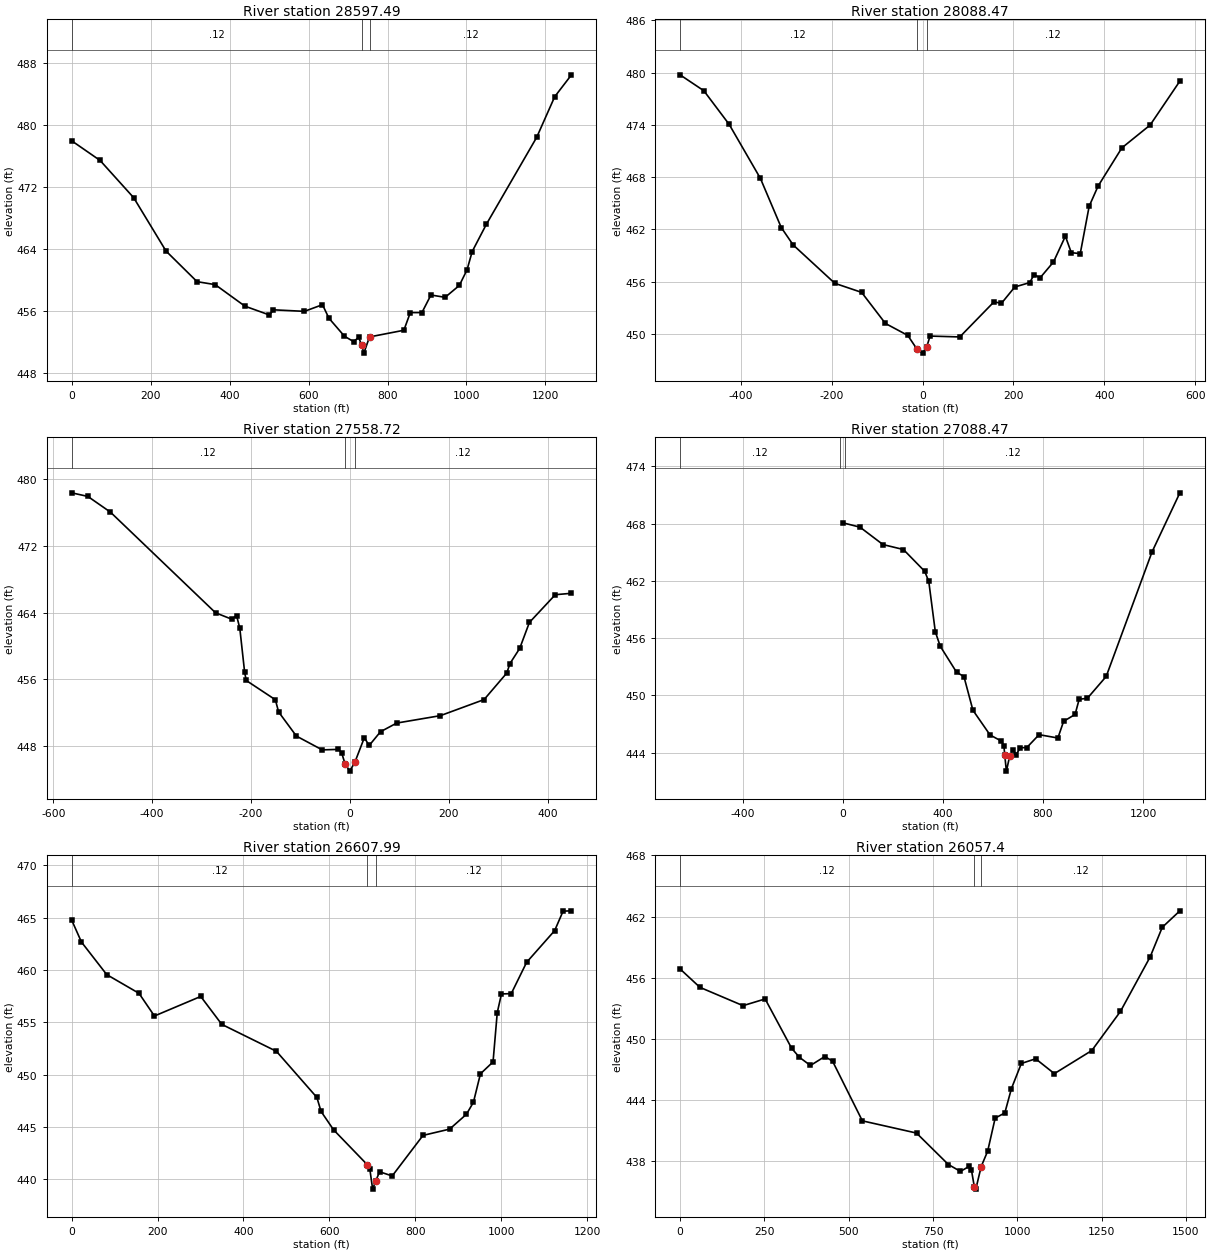
Type RM Length L Ch R = 1 ,28597.49,961.8607,992.4432,1014.874
XS GIS Cut Line= 3
2445277.87248677331261.6418622732445357.48486036330499.537415355
2445409.70194753330002.634209692
#Sta/Elev= 30
       0  477.92   72.04  475.38  157.18  470.57  239.04  463.69  317.63  459.74
  363.48  459.36  438.79  456.58  501.01  455.44  510.83  456.11  589.42  455.91
  635.27  456.77  651.64  455.02  690.94   452.7  713.86  452.01  726.96  452.54
  734.72  451.52  740.05  450.52  754.34  452.61  841.36  453.47  857.69  455.75
  887.08  455.75  909.94  458.02  945.86  457.72  981.78  459.25 1001.37  461.27
 1014.44  463.63 1050.36  467.15 1177.72  478.36 1223.44  483.61 1265.89  486.43
#Mann= 3 , 0 , 0
       0     .12       0  734.72    .045       0  754.34     .12       0
Bank Sta=734.72,754.34
XS Rating Curve= 0 ,0
Exp/Cntr=0.3,0.1

Type RM Length L Ch R = 1 ,28088.47,530.1951,529.7515,521.5281
XS GIS Cut Line= 3
   2445365.55834    331282.03848   2445698.06489     330863.9212
    2446051.6695    330421.27445
#Sta/Elev= 30
 -534.21  479.75 -481.77  477.92 -426.06  474.06 -357.23  467.85 -311.35  462.21
 -285.13  460.21 -193.37   455.8 -134.37  454.76  -81.93  451.19  -32.77  449.82
  -13.11  448.29       0  447.78    8.69  448.44   16.37  449.74   81.87  449.64
  157.19  453.67  173.57   453.5  203.04  455.38  235.79  455.88  245.61   456.8
  258.71  456.43  288.18  458.25  314.38  461.21  327.48  459.32  347.13  459.21
  366.78  464.65  386.43  466.97  438.83  471.36  501.05  473.98  566.54  479.03
#Mann= 3 , 0 , 0
 -534.21     .12       0  -13.11    .045       0    8.69     .12       0
Bank Sta=-13.11,8.69
XS Rating Curve= 0 ,0
Exp/Cntr=0.3,0.1

Type RM Length L Ch R = 1 ,27558.72,487.0486,470.2485,448.1023
XS GIS Cut Line= 3
   2445816.62436    331674.44583   2446062.24034    331238.62846
   2446312.94194    330793.78748
#Sta/Elev= 30
 -562.79  478.38  -530.1  477.95 -484.32  476.06 -271.79  463.98 -239.09  463.21
 -229.28  463.65 -222.74  462.13 -212.93  456.83 -209.66  455.85 -150.81  453.54
 -144.27  452.08  -108.3  449.18  -55.98  447.52  -23.25  447.58   -16.7  447.16
   -9.99  445.87    -.34  444.97   10.01  446.04   29.12  448.98   38.94  448.05
   61.85   449.7   94.59  450.74  182.96  451.63  271.34  453.56  317.17  456.74
  323.71  457.89  343.35   459.7  362.99  462.82  415.36  466.15  448.09  466.32
#Mann= 3 ,-1 , 0
 -562.79     .12       0   -9.99    .045       0   10.01     .12       0
Bank Sta=-9.99,10.01
XS Rating Curve= 0 ,0
Exp/Cntr=0.3,0.1

Type RM Length L Ch R = 1 ,27088.47,507.21,480.48,445.47
XS GIS Cut Line= 5
2446598.45744403 332046.491342442446484.05544186331603.105746269
2446492.90745828 331404.283637362446517.90970486331216.387031525
2446384.50905302330733.773495436
#Sta/Elev= 30
       0  468.08   68.69  467.62  160.27   465.8  242.04  465.28  327.08     463
  343.43  461.94   369.6  456.66  389.22  455.15  454.64  452.42  484.01  451.97
   519.9  448.44  588.41  445.85  634.09   445.2  643.88   444.7  646.85   443.8
  653.66  442.06  667.14  443.66   679.8  444.27  692.88   443.8  709.22  444.51
  735.36  444.53  784.38  445.88  859.57  445.53  882.48  447.28   928.3     448
  944.66  449.59  977.38  449.69 1052.66  451.98 1235.92  465.03 1347.19  471.22
#Mann= 3 ,-1 , 0
 -650.82     .12       0  -10.03    .045       0   10.02     .12       0
Bank Sta=646.85,667.14
XS Rating Curve= 0 ,0
Exp/Cntr=0.3,0.1

Type RM Length L Ch R = 1 ,26607.99,1471.443,1560.969,1625.222
XS GIS Cut Line= 4
2447125.02430427331704.0533790142446979.82938468331256.745874688
2446783.80713893331101.8925098482446435.84622069330827.010513693
#Sta/Elev= 30
       0  464.78   22.86  462.67   81.65  459.56  156.76  457.77  192.69   455.6
  300.46  457.47  349.45   454.8  476.77  452.22  570.85  447.81  580.59  446.47
  609.79  444.71  687.85  441.39  694.14  440.95  700.63  439.04  708.16  439.86
  716.85   440.7  746.18   440.3  817.91  444.18  879.86  444.78  918.99   446.2
  935.29  447.35  951.59  450.07  980.94  451.21  990.72  455.92  1000.5  457.71
 1023.32  457.74 1059.19  460.74  1124.4  463.77 1143.97  465.63 1163.53  465.66
#Mann= 3 , 0 , 0
       0     .12       0  687.85    .045       0  708.16     .12       0
Bank Sta=687.85,708.16
XS Rating Curve= 0 ,0
Exp/Cntr=0.3,0.1

Type RM Length L Ch R = 1 ,26057.4 ,491.59,468.93,439.39
XS GIS Cut Line= 5
2447196.44017194331622.1283460262447003.06227785330937.950908601
2447126.01478785330816.9019381112447185.35390803330763.992595106
2447057.15272085330261.008692935
#Sta/Elev= 30
       0  456.85   58.98  455.04  186.76  453.24  252.28   453.9  330.92  449.05
  353.85  448.17  386.62  447.36  429.21  448.24  452.14  447.79  540.61  441.92
  701.15  440.72  795.62  437.63  831.43  436.95  857.48  437.45  863.99   437.1
  872.96  435.37  877.01  435.21  892.95  437.43  912.14  438.94   934.4  442.19
  963.02   442.7  982.61  445.09 1011.99  447.56 1054.43  448.02 1109.93  446.56
 1220.92  448.83  1305.8  452.67 1393.94  458.03 1429.85  460.94 1482.09  462.56
#Mann= 3 , 0 , 0
       0     .12       0  872.96    .045       0  892.95     .12       0
Bank Sta=872.96,892.95
XS Rating Curve= 0 ,0
Exp/Cntr=0.3,0.1

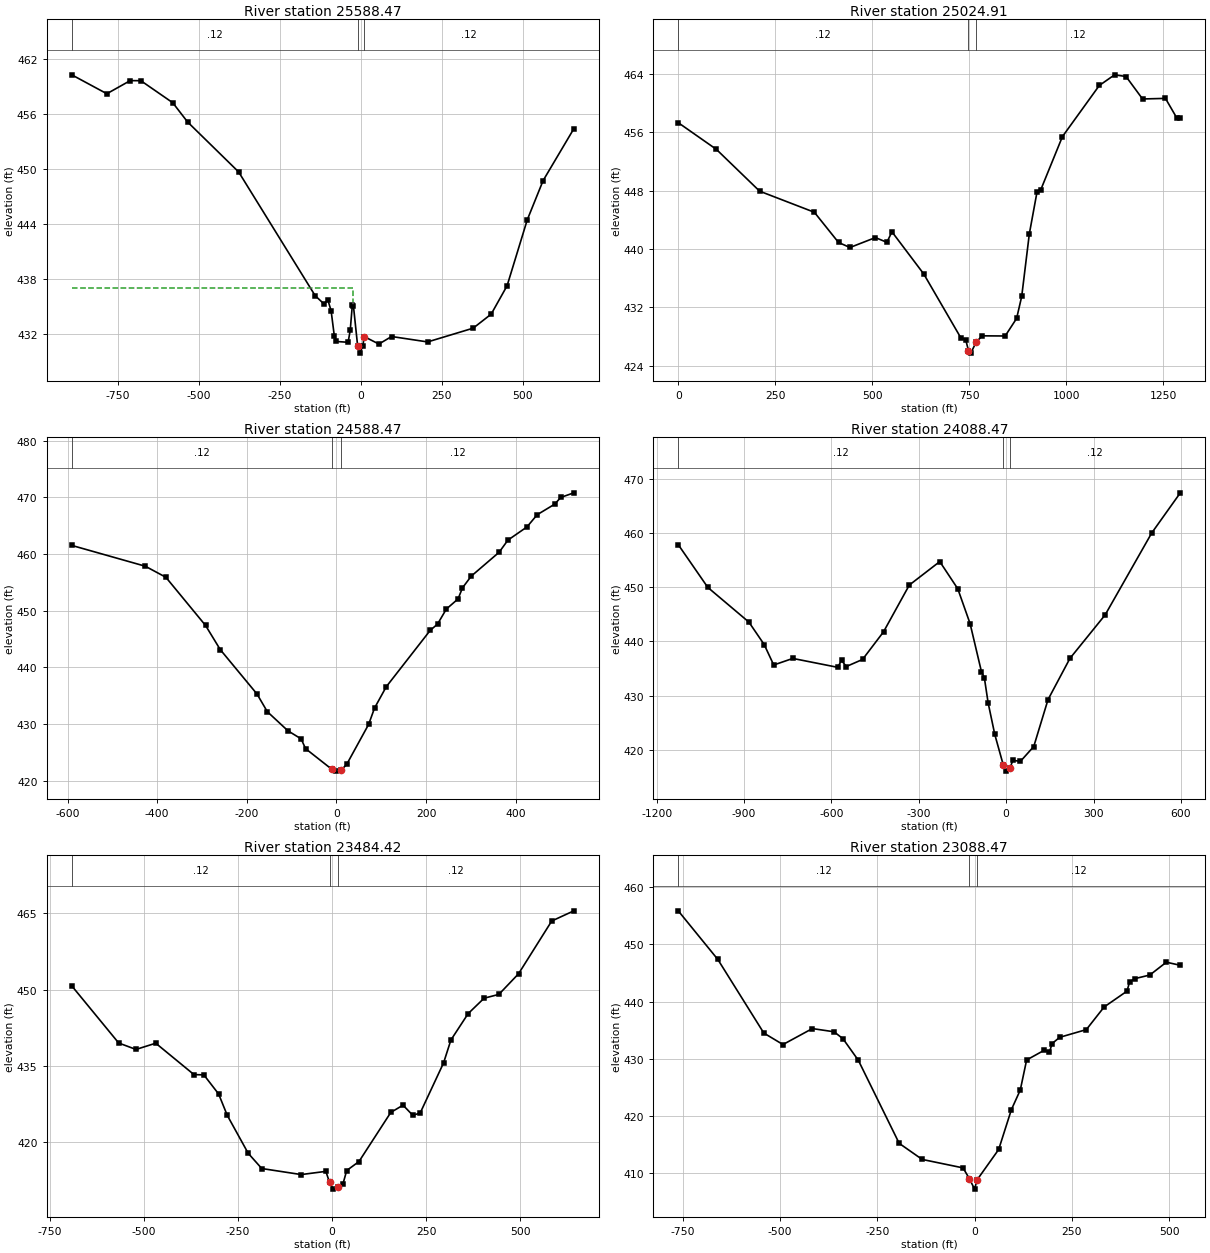
Type RM Length L Ch R = 1 ,25588.47,984.1338,1000,953.161
XS GIS Cut Line= 3
   2447588.68315    331818.69619    2447554.3325    330927.41615
   2447528.63078    330270.83282
#Sta/Elev= 30
 -891.94  460.28 -783.73  458.22 -711.59  459.65 -678.79  459.64 -580.42  457.24
 -534.51  455.14 -377.11   449.7 -141.01  436.22 -114.77  435.35 -101.66  435.73
  -91.82  434.58  -81.98  431.85  -75.42  431.23  -39.35  431.14  -32.79  432.46
  -26.23  435.25  -22.95  435.11   -9.98  430.75   -3.28  429.96    6.54  430.78
    9.81  431.77   55.57  430.95    94.8  431.77  205.95  431.18  346.52  432.68
   402.1  434.21  451.13   437.3  513.25  444.47  562.28  448.76  657.09  454.41
#Mann= 3 , 0 , 0
 -891.94     .12       0   -9.98    .045       0    9.81     .12       0
#XS Ineff= 2 , 0
          -25.46  437.04
Permanent Ineff=
       F       F
Bank Sta=-9.98,9.81
XS Rating Curve= 0 ,0
Exp/Cntr=0.3,0.1

Type RM Length L Ch R = 1 ,25024.91,434.13,436.44,383.71
XS GIS Cut Line= 3
2447659.24830145331456.3281526862447971.49078719 330236.03794235
2447981.69221036330202.540305942
#Sta/Elev= 30
       0   457.3   98.41  453.64  209.93  447.91  350.98  445.02  413.31  440.88
  442.83  440.19  508.43  441.55  537.96   440.9  551.08  442.34  633.08  436.56
  728.21  427.85  741.33  427.53  748.35  426.07  754.45  425.71  768.21  427.23
  783.97  428.08  843.02  428.06  872.54  430.47  885.66  433.49  905.34  442.07
  925.02  447.77  934.86  448.11  990.63  455.39 1085.75   462.4 1125.12  463.86
 1154.64  463.63 1197.28  460.55 1256.33  460.63 1285.07  457.99 1294.62  457.97
#Mann= 3 , 0 , 0
       0     .12       0  748.35    .045       0  768.21     .12       0
Bank Sta=748.35,768.21
XS Rating Curve= 0 ,0
Exp/Cntr=0.3,0.1

Type RM Length L Ch R = 1 ,24588.47,506.0794,499.9999,460.9907
XS GIS Cut Line= 3
   2448208.47489    331462.79336   2448182.57599    330872.87886
   2448156.56489    330343.82546
#Sta/Elev= 30
 -590.48  461.52 -426.46  457.85 -380.53   455.9 -291.96  447.39 -259.16  443.13
 -177.14  435.29 -154.18  432.18 -108.26  428.81  -78.73  427.38  -68.89  425.66
   -9.91  421.99       0  421.69   10.19  421.84   22.89  422.88   71.93  429.95
   85.01  432.82  111.17  436.58  209.26  446.53  225.61  447.64  245.23  450.29
  271.39  452.08  281.19  454.03  300.81   456.1  362.94  460.31  382.56  462.45
  425.06  464.78  447.95  466.94  487.19  468.81  500.26  469.98  529.69   470.8
#Mann= 3 ,-1 , 0
 -590.48     .12       0   -9.91    .045       0   10.19     .12       0
Bank Sta=-9.91,10.19
XS Rating Curve= 0 ,0
Exp/Cntr=0.3,0.1

Type RM Length L Ch R = 1 ,24088.47,564.6619,604.0481,542.247
XS GIS Cut Line= 4
   2448810.90545    331983.62697   2448748.79238    331139.94591
   2448603.27496    330900.69606   2448292.50196    330389.74302
#Sta/Elev= 30
-1125.99  457.83-1024.35  449.95 -883.35  443.57 -830.89  439.44  -798.1  435.67
 -732.52  436.88 -578.41  435.24  -565.3  436.52  -548.9  435.39 -493.16  436.69
 -421.02  441.78 -332.49  450.39 -227.93  454.71 -166.06   449.7 -123.73  443.27
  -84.66   434.4  -74.89  433.34  -61.87   428.7  -39.07  422.89   -9.77  417.24
       0  416.13   13.07  416.66   22.88  418.12   49.02  417.93   94.77  420.66
  143.79   429.3  218.95  436.88  339.87  444.89     500  459.99  598.04  467.37
#Mann= 3 , 0 , 0
-1125.99     .12       0   -9.77    .045       0   13.07     .12       0
Bank Sta=-9.77,13.07
XS Rating Curve= 0 ,0
Exp/Cntr=0.3,0.1

Type RM Length L Ch R = 1 ,23484.42,372.0689,395.9521,408.801
XS GIS Cut Line= 5
    2449330.2922    331187.04129   2449270.74442    330914.75082
   2448990.08553    330617.10575   2448829.43297    330446.73011
   2448470.91695    330245.20098
#Sta/Elev= 30
 -691.17  450.73 -566.56  439.47 -520.65   438.2 -468.19  439.43 -366.62  433.24
 -340.44  433.19 -301.17  429.42 -278.26  425.21 -222.62  417.73 -186.62  414.73
  -81.89  413.54  -16.43  414.17   -6.62  411.99    3.16  410.67   16.17  411.12
   29.18  411.75   38.94  414.34   71.46   416.1  156.03  425.79  188.55  427.22
  214.57  425.21   234.1  425.68  296.11  435.54   315.7  440.07  361.39  445.26
  403.83   448.3     443  449.05  495.22  453.11  583.35  463.51  642.11  465.52
#Mann= 3 , 0 , 0
 -691.17     .12       0   -6.62    .045       0   16.17     .12       0
Bank Sta=-6.62,16.17
XS Rating Curve= 0 ,0
Exp/Cntr=0.3,0.1

Type RM Length L Ch R = 1 ,23088.47,516.8025,500,476.356
XS GIS Cut Line= 3
   2449449.64958    331239.12452   2449330.22888    330487.52727
   2449246.06009    329965.80751
#Sta/Elev= 30
 -761.03  455.88 -659.34  447.38 -541.25  434.52 -492.04  432.51  -416.6   435.3
 -360.83  434.74 -337.87  433.52 -298.51  429.76 -193.54  415.24 -134.49  412.43
  -29.52  410.95  -13.12  409.05       0  407.24    6.52  408.86   61.98  414.17
    94.6  421.13  117.44  424.56  133.75  429.81  179.42  431.53  192.47  431.18
  198.99  432.67  218.56  433.77  287.07  435.12  332.74  439.07  391.46  441.84
  397.98  443.39  411.03  444.02  450.17  444.66  492.58   446.9  528.47  446.36
#Mann= 3 , 0 , 0
 -761.03     .12       0  -13.12    .045       0    6.52     .12       0
Bank Sta=-13.12,6.52
XS Rating Curve= 0 ,0
Exp/Cntr=0.3,0.1

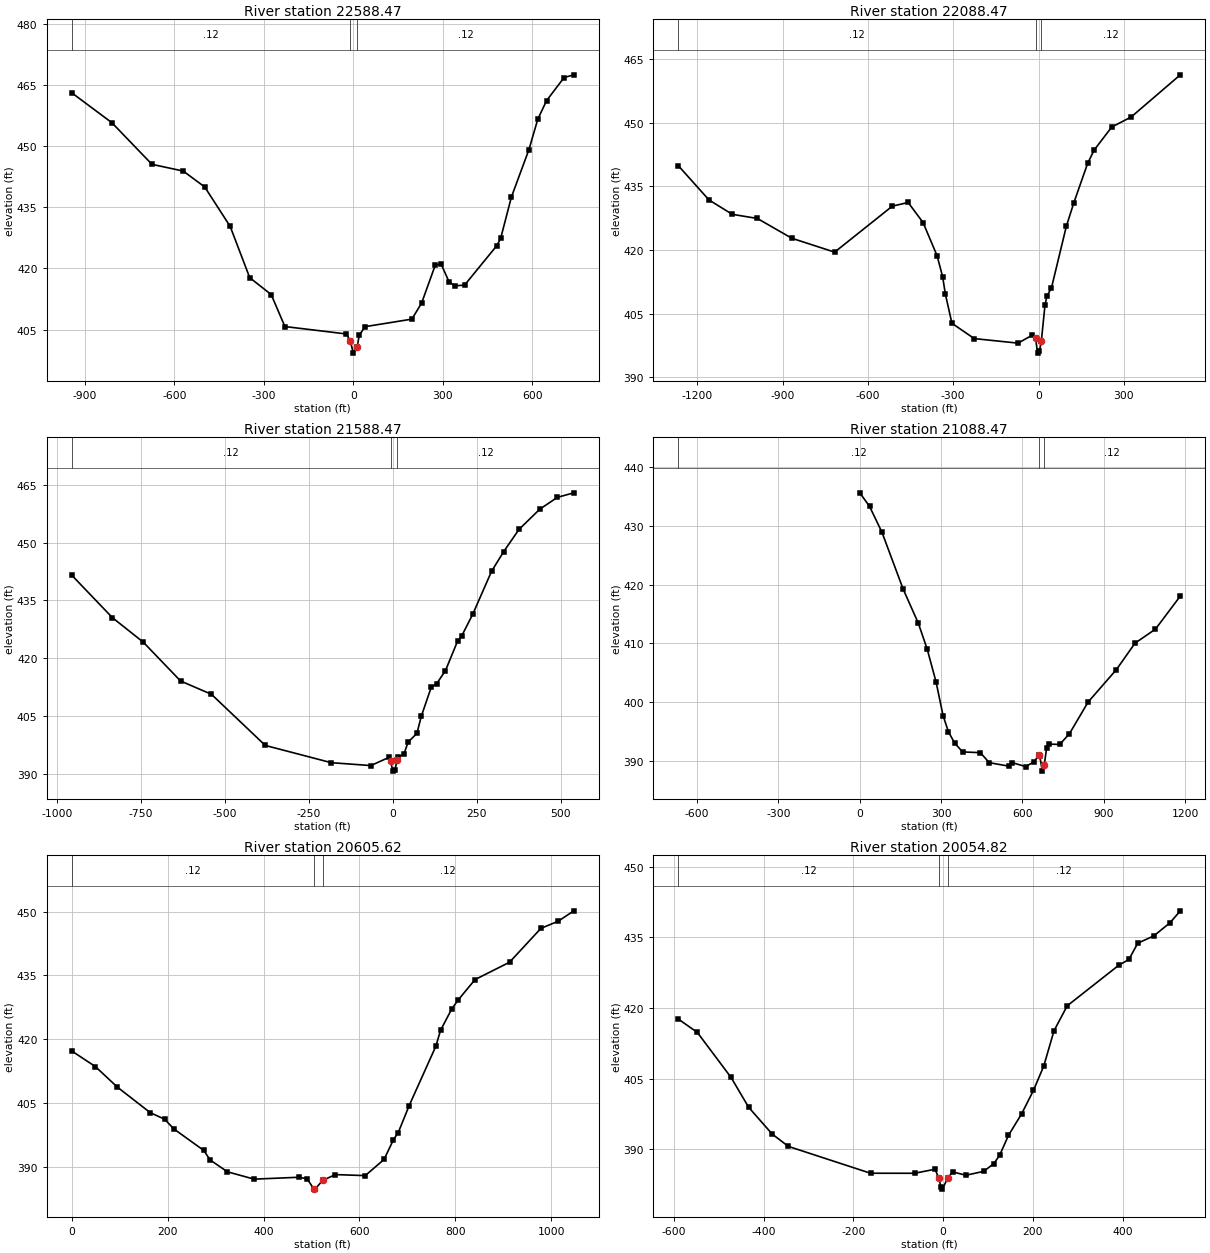
Type RM Length L Ch R = 1 ,22588.47,474.5533,500,520.5178
XS GIS Cut Line= 4
   2449861.97618    330987.38847    2449926.9872    330411.24035
   2449659.20985    330165.41243   2449108.93799    329672.28415
#Sta/Elev= 30
 -943.31  463.09    -809  455.77  -674.7  445.55 -569.88   443.9 -497.81  439.99
 -412.64  430.33 -347.13  417.75 -275.08  413.59 -229.24  405.75  -22.92  403.93
   -9.82  402.17       0  399.23   13.08  400.71   19.62  403.58   39.23  405.72
  196.17  407.57  228.86  411.51  274.64  420.83  294.25  421.07  320.41  416.78
  340.03  415.75  372.72  415.91  480.61  425.58  493.69  427.39  529.65  437.52
  588.51  449.18  617.93  456.59  647.36  461.16  706.21  466.85   738.9  467.51
#Mann= 3 , 0 , 0
 -943.31     .12       0   -9.82    .045       0   13.08     .12       0
Bank Sta=-9.82,13.08
XS Rating Curve= 0 ,0
Exp/Cntr=0.3,0.1

Type RM Length L Ch R = 1 ,22088.47,522.0925,499.9998,475.454
XS GIS Cut Line= 3
   2450145.83027     331237.3883   2450067.78351     329972.7468
   2450034.60543    329475.15495
#Sta/Elev= 30
-1267.05  439.92   -1159  431.82-1077.15  428.42 -988.76  427.44 -867.62  422.77
 -717.01  419.49 -514.02  430.35 -458.36  431.21 -405.98  426.47 -356.87  418.67
 -337.22  413.71  -327.4  409.52 -304.48  402.69 -225.91  399.08  -72.03  398.01
  -22.92  399.85  -10.09  399.11   -3.27  395.65    3.26  396.04      10   398.5
   22.82  407.01   29.33  409.06   45.63  411.07   97.78  425.57  123.86  431.08
  172.75  440.44  195.57  443.58   257.5  449.02  325.95   451.4   498.7  461.35
#Mann= 3 ,-1 , 0
-1267.05     .12       0  -10.09    .045       0      10     .12       0
Bank Sta=-10.09,10
XS Rating Curve= 0 ,0
Exp/Cntr=0.3,0.1

Type RM Length L Ch R = 1 ,21588.47,491.2853,500,497.9432
XS GIS Cut Line= 3
   2451232.63584    330535.99961   2450521.21272    329896.45562
   2450119.06097    329536.65844
#Sta/Elev= 30
 -956.63  441.53 -835.41  430.52 -743.68  424.19 -632.29  414.11 -540.56  410.68
 -380.03  397.42 -183.46  392.95  -65.52   392.2   -9.83  394.38   -6.55  393.32
       0  390.76    6.54  391.11   13.08  393.66   16.35  394.51    32.7  395.07
   45.78  398.29   71.95  400.54   85.03  404.99  114.46  412.46  130.81  413.42
  156.98  416.81  192.95  424.41  206.03  425.89  238.74   431.5  294.33  442.53
  330.31  447.62  376.09  453.39  438.23  458.65  490.56  461.71  539.61  462.88
#Mann= 3 , 0 , 0
 -956.63     .12       0   -6.55    .045       0   13.08     .12       0
Bank Sta=-6.55,13.08
XS Rating Curve= 0 ,0
Exp/Cntr=0.3,0.1

Type RM Length L Ch R = 1 ,21088.47,423.75,482.85,483.79
XS GIS Cut Line= 5
2451324.64976327330167.9439184372450932.15678185 329681.97573027
2450896.30580369329653.4419946822450861.41020419329626.854449436
2450570.09057686329260.828934774
#Sta/Elev= 30
       0  435.61   35.98  433.31   81.76  428.91  160.26  419.19  215.86  413.43
  248.56  409.02  281.27  403.44  307.43  397.66  327.05  394.93  349.95  393.01
  379.38  391.51  444.79  391.38   477.5  389.68  549.45  389.09  562.53  389.68
  611.59  389.02  644.31  389.86  659.45  391.02  663.95  390.75  673.63  388.24
  680.28  389.26  689.29  392.23  698.69  392.84  737.26  392.78  773.25   394.6
  841.95  399.99  946.63  405.53 1015.33  410.03 1090.57  412.41 1182.17  418.04
#Mann= 3 , 0 , 0
 -669.47     .12       0  659.45    .045       0  680.28     .12       0
Bank Sta=659.45,680.28
XS Rating Curve= 0 ,0
Exp/Cntr=0.3,0.1

Type RM Length L Ch R = 1 ,20605.62,1059.618,1101.115,1069.352
XS GIS Cut Line= 5
2451464.38111112 329887.703993352451247.26081043329520.951446027
2451243.39139561329433.3371199372451237.27821887329345.170301527
2451014.22912428328960.232423097
#Sta/Elev= 30
       0  417.21   49.18  413.55   95.08  408.71  163.92  402.68  193.43  401.17
   213.1  398.85  275.39   393.8  288.51  391.57  324.57  388.78   380.3  387.05
  474.92   387.5  491.17  387.09  504.27  384.84  507.41   384.7  523.31  386.76
  549.91  388.12  612.09  387.88  651.35  391.69  670.98  396.34  680.79  397.98
  703.69  404.36   759.3  418.32  769.12  422.07  792.01     427   805.1  429.11
  841.08  434.02  913.05   438.1  978.48  446.07 1014.46  447.75 1047.17   450.2
#Mann= 3 , 0 , 0
       0     .12       0  504.27    .045       0  523.31     .12       0
Bank Sta=504.27,523.31
XS Rating Curve= 0 ,0
Exp/Cntr=0.3,0.1

Type RM Length L Ch R = 1 ,20054.82,447.9204,466.3531,479.5653
XS GIS Cut Line= 3
   2451838.01882    329852.91043   2451693.06537    329282.75671
   2451553.42162    328771.74035
#Sta/Elev= 30
 -589.96  417.65 -547.47   414.8  -472.3  405.22 -433.08  398.87 -380.79  393.19
 -344.84  390.57 -161.82  384.86  -63.77  384.85  -18.01  385.71  -10.11  383.88
   -4.94  381.96   -1.67  381.48      10  383.82   21.22  385.15   50.65  384.43
   89.89  385.25  112.78  386.89  125.86   388.7  145.48  392.92  174.91  397.52
  201.07  402.48  223.96  407.64  246.85  415.16  276.29  420.46  390.74  429.06
  413.63  430.31  433.25  433.76  469.22  435.33  505.19  438.12  528.08  440.65
#Mann= 3 ,-1 , 0
 -589.96     .12       0  -10.11    .045       0      10     .12       0
Bank Sta=-10.11,10
XS Rating Curve= 0 ,0
Exp/Cntr=0.3,0.1

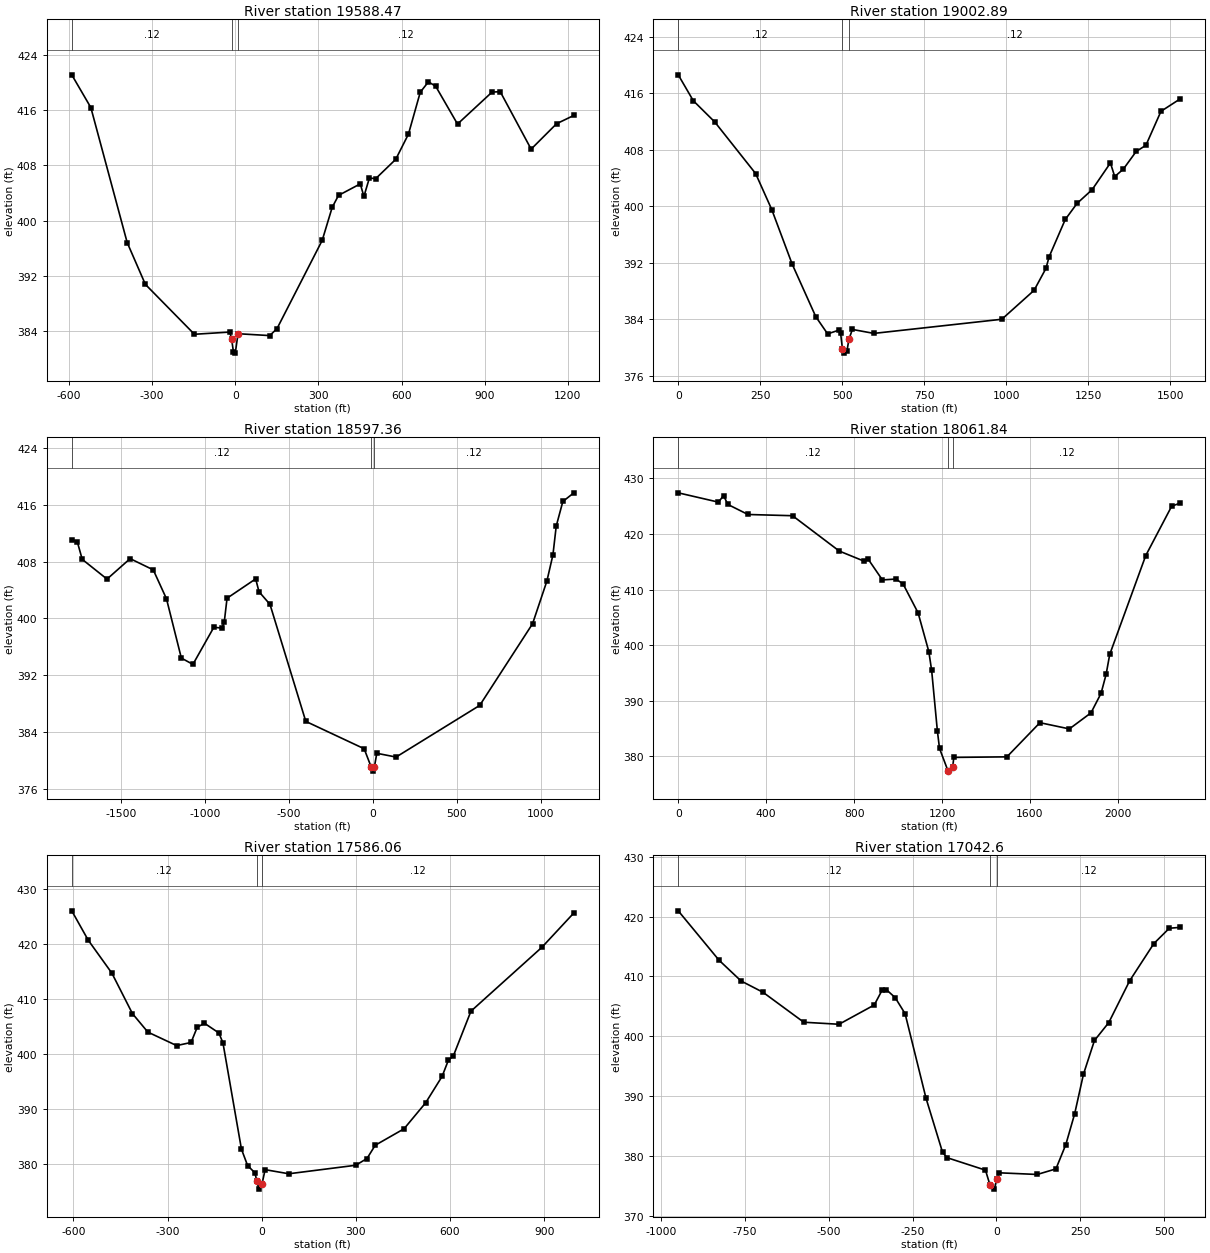
Type RM Length L Ch R = 1 ,19588.47,987.8606,991.1049,991.9768
XS GIS Cut Line= 4
   2451946.88638    329852.22637   2452113.62686    329286.02245
   2452231.76245    328891.50651   2452090.98353    328093.54584
#Sta/Elev= 30
 -590.25  421.12 -521.38  416.38 -390.22  396.83 -324.63  390.78 -147.56  383.55
  -19.67  383.87  -13.12  382.82   -6.56  380.96       0  380.82    9.81  383.63
   124.2  383.36  150.35  384.35  313.77  397.15  349.72  401.92   372.6  403.66
  451.19  405.33  464.31  403.51  483.99  406.17  506.96  406.09  579.13  408.88
  625.06  412.53   667.7   418.6  697.23  420.11  723.47  419.46   802.2  413.99
  926.86  418.62  956.39  418.68 1067.92  410.36 1159.78  414.04 1222.11  415.24
#Mann= 3 ,-1 , 0
 -590.25     .12       0  -13.12    .045       0   10.14     .12       0
Bank Sta=-13.12,9.81
XS Rating Curve= 0 ,0
Exp/Cntr=0.3,0.1

Type RM Length L Ch R = 1 ,19002.89,406.6,405.53,404.75
XS GIS Cut Line= 3
2452481.72258036329958.7012266812452657.57065386329471.594917431
2453018.37439419 328524.77397643
#Sta/Elev= 30
       0  418.59   45.89  414.93  111.44  411.92  235.99  404.63  285.16  399.54
  347.44  391.82  419.54  384.38   455.6  381.95  491.65  382.51  494.93  382.13
  500.66  379.87  504.77  379.23   514.6  379.57   520.6  381.19  530.99  382.58
  596.57  382.02  986.79  384.02 1085.16  388.11 1121.23   391.2 1131.07  392.86
 1180.25  398.13 1216.32  400.41 1262.23  402.35 1317.97  406.13 1331.09   404.2
 1357.32  405.25 1396.67  407.76 1426.18  408.62 1472.09  413.43 1531.11   415.2
#Mann= 3 , 0 , 0
       0     .12       0  500.66    .045       0   520.6     .12       0
Bank Sta=500.66,520.6
XS Rating Curve= 0 ,0
Exp/Cntr=0.3,0.1

Type RM Length L Ch R = 1 ,18597.36,983.5831,1011.305,1006.18
XS GIS Cut Line= 3
   2452488.99422     331331.4908   2453032.29661    329624.81115
   2453428.66458    328492.08113
#Sta/Elev= 30
-1792.66  411.07-1759.86   410.8-1730.34  408.32-1582.72  405.54-1444.95  408.42
-1307.17  406.84-1228.44  402.77-1139.87  394.43-1070.99  393.54 -946.33  398.76
 -897.13  398.65 -884.01  399.53 -867.61  402.85 -697.03  405.57 -677.35  403.77
 -611.74  401.98 -398.52  385.52   -50.8  381.67  -10.06  379.17    1.55  378.52
   10.05   379.1   24.64  381.03   139.4   380.5  637.79  387.77  952.57  399.26
 1037.82  405.26 1073.89  408.95 1093.56     413 1132.91  416.46 1198.48  417.68
#Mann= 3 ,-1 , 0
-1792.66     .12       0  -10.06    .045       0   10.05     .12       0
Bank Sta=-10.06,10.05
XS Rating Curve= 0 ,0
Exp/Cntr=0.3,0.1

Type RM Length L Ch R = 1 ,18061.84,470.52,475.78,476.28
XS GIS Cut Line= 5
2453605.89257611 331002.671251612453383.54361136330101.025089026
2453480.77307568329801.3908457762453635.92368403329323.259584188
 2453866.3093781328837.740870193
#Sta/Elev= 30
       0  427.42  183.12  425.74     206  426.93  225.62  425.33  317.18  423.52
  519.92   423.3  732.46  416.94  846.91  415.09  863.26  415.52  928.66  411.74
  990.36   411.9 1022.84  411.01 1091.04  405.81 1139.75  398.85 1152.74  395.44
 1178.72  384.56 1188.46  381.41 1227.42  377.32 1248.58   378.1 1253.47  379.79
 1495.01  379.89 1645.16  386.04 1779.12  384.92 1877.42  387.81  1923.3  391.33
 1946.24  394.74 1962.62  398.32 2126.46  416.12 2244.43  425.01 2283.75  425.58
#Mann= 3 , 0 , 0
       0     .12       0 1227.42    .045       0 1248.58     .12       0
Bank Sta=1227.42,1248.58
XS Rating Curve= 0 ,0
Exp/Cntr=0.3,0.1

Type RM Length L Ch R = 1 ,17586.06,532.2178,543.4628,553.2307
XS GIS Cut Line= 3
   2453695.30217    330488.78252   2453878.99308    330018.75688
   2454283.84398     329000.9351
#Sta/Elev= 30
 -605.45  426.11 -553.02  420.76 -477.65  414.75 -412.11  407.37 -362.95     404
  -271.2  401.54 -225.32  402.11 -205.66  404.88 -182.72  405.62 -136.85  403.85
 -123.74  402.06  -64.73  382.66  -45.05  379.66  -22.09  378.36  -15.53  376.85
   -8.97  375.37     .87  376.33   10.71  378.92   86.14  378.17  299.31  379.72
  335.38  380.95  361.62  383.37  453.45  386.37  522.32  391.11  574.79  395.93
  594.47  398.84  610.87   399.7  666.62  407.81  892.92  419.47  994.58  425.72
#Mann= 3 , 0 , 0
 -605.45     .12       0  -15.53    .045       0     .87     .12       0
Bank Sta=-15.53,0.87
XS Rating Curve= 0 ,0
Exp/Cntr=0.3,0.1

Type RM Length L Ch R = 1 ,17042.6 ,518.2399,526.295,526.4755
XS GIS Cut Line= 3
   2453782.76952    330886.35554    2454387.5754    330156.42754
   2454759.88535    329754.97165
#Sta/Elev= 30
 -947.94  420.96 -826.58  412.72 -760.97  409.25 -695.37  407.35 -574.01  402.35
 -469.05  402.01 -364.09  405.23 -341.13  407.66 -328.01  407.79 -301.77  406.46
 -272.24  403.78 -209.92  389.66 -160.72  380.63  -147.6  379.73   -32.8  377.64
  -19.68  375.21   -6.56  374.47     .77  376.15    6.56   377.2  121.31  376.92
  177.04  377.85  206.55  381.92  232.78  387.04  259.01  393.66  291.79   399.3
  334.42  402.29  396.71  409.28  468.84   415.5  514.74  418.05  547.52   418.2
#Mann= 3 ,-1 , 0
 -947.94     .12       0  -19.68    .045       0     .77     .12       0
Bank Sta=-19.68,0.77
XS Rating Curve= 0 ,0
Exp/Cntr=0.3,0.1