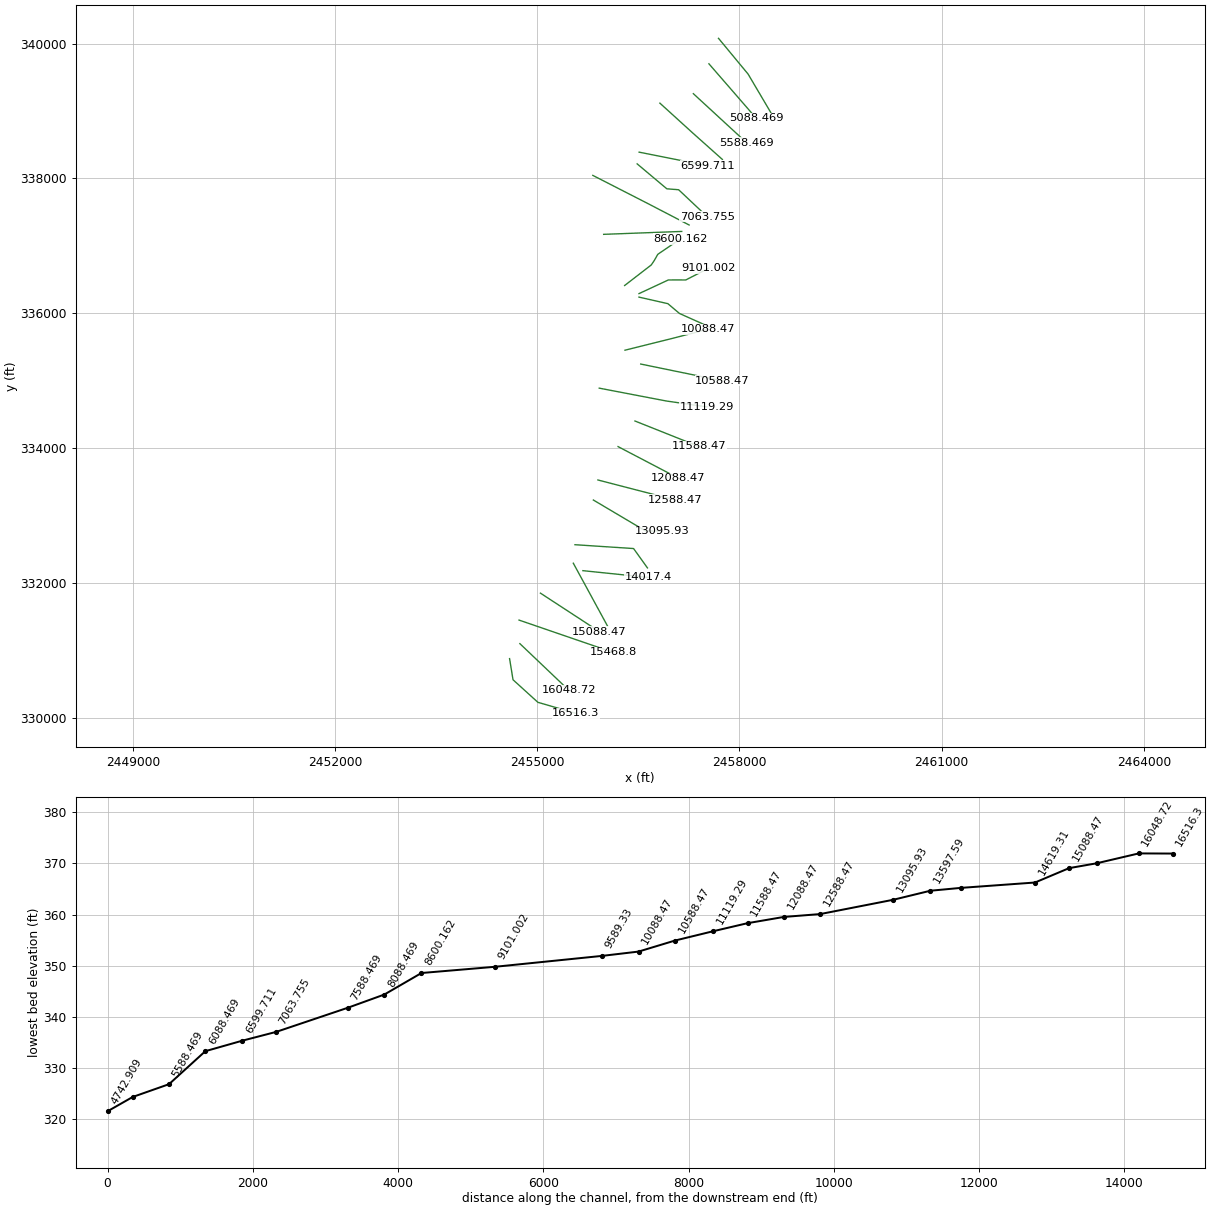
HEC-RAS study RattlesnakeRun.prj: Basic Project File

--- RattlesnakeRun.g01 (geometry) --- (continued)

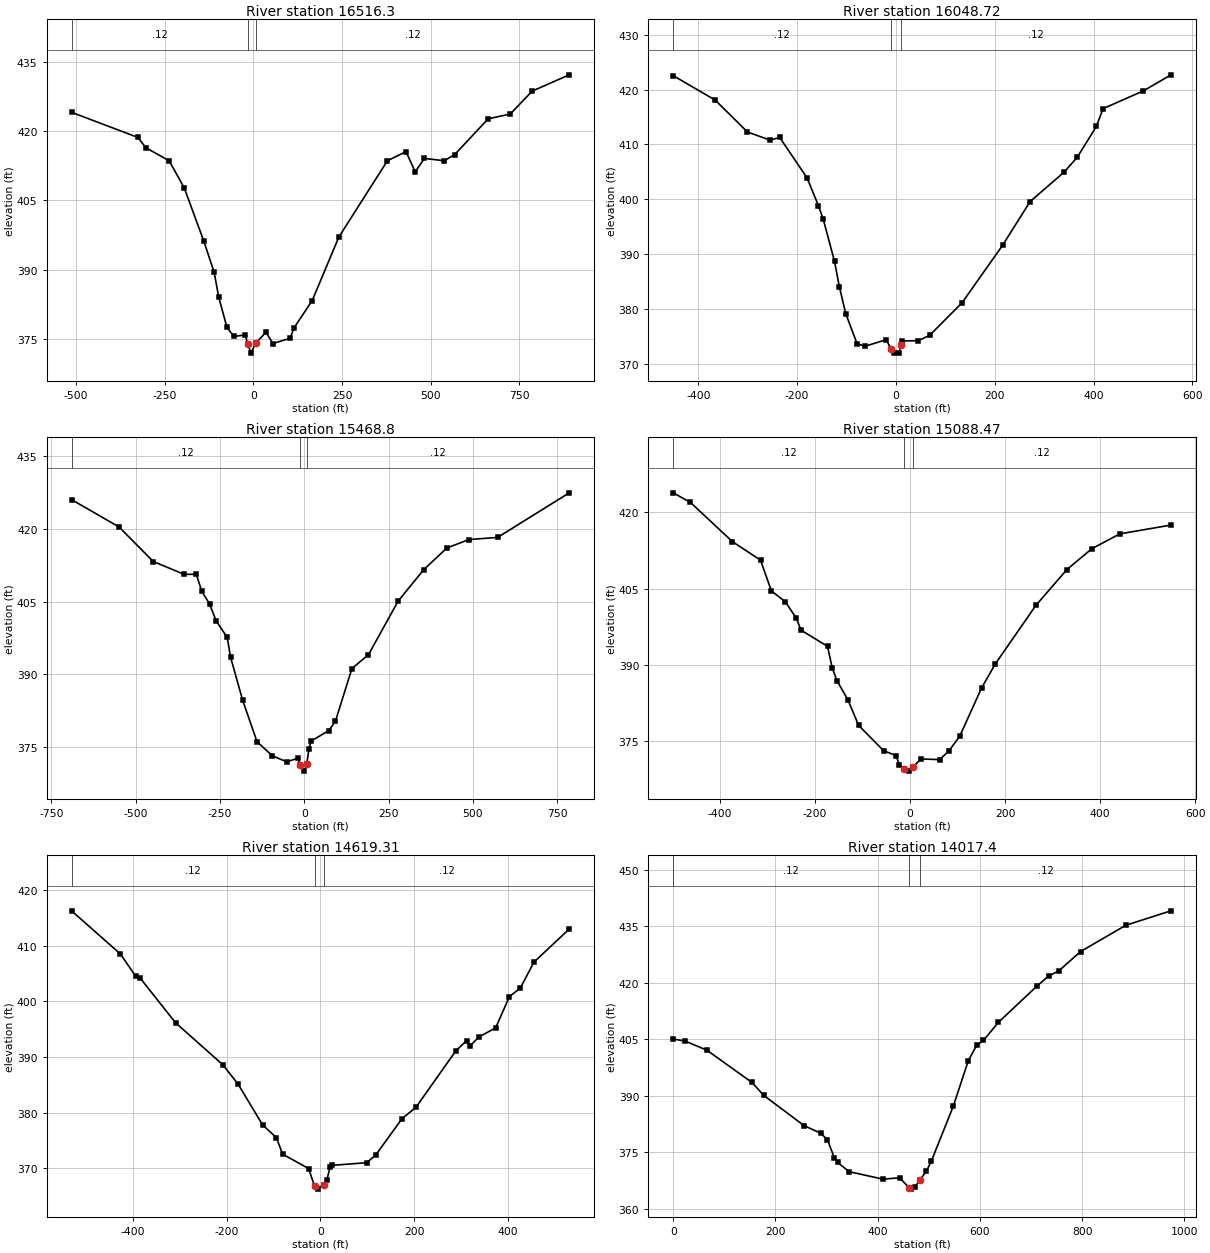
Type RM Length L Ch R = 1 ,16516.3 ,467.5559,467.5835,465.4793
XS GIS Cut Line= 5
   2454590.14815    330875.85195   2454641.22154    330562.10455
   2454797.41677    330420.47261   2455009.96162    330227.74498
   2455574.52315    330063.35194
#Sta/Elev= 30
  -512.8  424.04 -326.01  418.61 -303.07  416.37 -237.53  413.55 -194.93  407.67
 -139.78  396.15 -110.59   389.4  -97.61  383.99  -74.91  377.59  -55.44  375.53
     -23  375.87  -16.52     374   -6.79  371.93    6.19  374.06   35.48  376.45
   55.05  374.01  103.95  375.15  113.73  377.31   165.9  383.31  240.89  397.04
  377.97  413.56  430.24  415.53  456.37  411.18   482.5  414.06  538.04  413.56
  567.44  414.88  662.17  422.64  724.24  423.66  786.31  428.63  890.84  432.15
#Mann= 3 , 0 , 0
  -512.8     .12       0  -16.52    .045       0    6.19     .12       0
Bank Sta=-16.52,6.19
XS Rating Curve= 0 ,0
Exp/Cntr=0.3,0.1

Type RM Length L Ch R = 1 ,16048.72,561.5841,579.9158,589.2054
XS GIS Cut Line= 3
   2454743.11241    331097.70912   2455107.05952    330751.14321
   2455472.52336    330403.13308
#Sta/Elev= 30
 -450.71  422.54 -365.86   418.1  -300.6  412.28 -254.91   410.8 -235.33  411.28
 -179.85   403.9 -157.01  398.86 -147.22  396.38 -124.37  388.69 -114.58  384.07
 -101.53  379.12  -78.69  373.67  -62.37  373.22  -19.95  374.41   -9.94  372.74
   -3.63  371.96    6.16  372.03   10.01  373.49   12.69  374.17   45.32  374.24
   68.23  375.21  133.77  381.15   215.7  391.62  271.41  399.59  340.22  404.96
  366.44  407.63  405.76  413.32  418.87  416.53  500.79  419.78   556.5   422.7
#Mann= 3 ,-1 , 0
 -450.71     .12       0   -9.94    .045       0   10.01     .12       0
Bank Sta=-9.94,10.01
XS Rating Curve= 0 ,0
Exp/Cntr=0.3,0.1

Type RM Length L Ch R = 1 ,15468.8 ,385.0684,380.3336,370.2084
XS GIS Cut Line= 3
   2454730.33915    331447.49549   2455377.29717    331225.24331
   2456126.17231     330968.3288
#Sta/Elev= 30
    -690  426.05 -549.26  420.41  -447.8  413.28 -356.15  410.63 -320.15  410.64
 -303.78  407.11 -280.87  404.53 -261.23  401.03  -228.5  397.63 -218.68  393.59
 -182.68  384.66 -140.13  376.11  -94.31  373.17  -51.76  371.95  -19.03   372.7
  -12.48  371.32     .61  370.03    7.15  371.42   13.69  374.52   20.24  376.23
   72.58  378.38   92.21   380.3  141.29   391.2  190.36  394.06  278.69  405.15
  353.94  411.58  422.64  416.06  488.07  417.81  573.13  418.25  785.78  427.45
#Mann= 3 , 0 , 0
    -690     .12       0  -12.48    .045       0    7.15     .12       0
Bank Sta=-12.48,7.15
XS Rating Curve= 0 ,0
Exp/Cntr=0.3,0.1

Type RM Length L Ch R = 1 ,15088.47,478.392,469.1619,451.1669
XS GIS Cut Line= 3
   2455047.78339    331847.32639   2455465.27764    331574.83185
   2455925.21996    331274.63101
#Sta/Elev= 30
 -498.55  423.84 -462.47  421.96 -373.91  414.23 -314.88   410.6 -291.92  404.54
  -262.4  402.39 -239.44  399.15  -229.6  396.82 -173.84  393.64    -164  389.45
 -154.16  386.91  -131.2  383.17 -108.24  378.07  -55.76  373.11  -29.52  372.14
  -22.96  370.38  -13.12  369.53   -3.28  369.08    6.54  369.94   22.89  371.48
   62.12  371.34   81.73  373.06  104.62  375.96  150.39  385.43  179.81  390.23
  264.81  401.69   330.2  408.75  382.51  412.83  441.36  415.76  549.24   417.5
#Mann= 3 , 0 , 0
 -498.55     .12       0  -13.12    .045       0    6.54     .12       0
Bank Sta=-13.12,6.54
XS Rating Curve= 0 ,0
Exp/Cntr=0.3,0.1

Type RM Length L Ch R = 1 ,14619.31,975.3208,1021.72,1039.241
XS GIS Cut Line= 3
   2455535.83294    332291.14768   2455785.29767    331832.88383
   2456043.39361    331358.76503
#Sta/Elev= 30
 -530.79  416.25 -426.44  408.49 -393.83  404.48 -384.04  404.13 -309.04  396.15
 -207.95  388.59 -175.34  385.09 -123.16  377.78  -93.81  375.52  -80.77  372.56
  -25.33  369.97  -12.29  366.79   -5.75  366.27    7.33  367.09   13.88  367.92
   20.42  370.19   23.69  370.53   98.94  371.02  118.57  372.47  174.18  378.94
  203.63  380.95  288.69  391.09  311.59  392.93  318.14  391.89  337.77  393.58
  373.75  395.24   403.2  400.86   426.1  402.35  455.54  407.05  530.79  412.99
#Mann= 3 , 0 , 0
 -530.79     .12       0  -12.29    .045       0    7.33     .12       0
Bank Sta=-12.29,7.33
XS Rating Curve= 0 ,0
Exp/Cntr=0.3,0.1

Type RM Length L Ch R = 1 ,14017.4 ,415.81,419.81,419.35
XS GIS Cut Line= 3
2455678.46192178332180.6429770142456148.34746495332132.138480857
 2456647.2116247332080.641864687
#Sta/Elev= 30
       0   405.1   22.96  404.57   65.61  402.15  154.18  393.55  177.14  390.11
  255.87   382.1  288.68  380.06   301.8  378.33  314.92  373.62  321.48  372.31
  344.45  369.85  410.05  367.88  442.86  368.22  462.25  365.52  465.82  365.22
  472.38  365.67  483.09  367.76  495.33  369.98  505.16  372.71  547.77  387.19
  577.27  399.32  593.66  403.45  606.78  404.71  636.28  409.54  711.67  419.17
  734.61  421.86  754.28  423.19  796.89  428.33  885.39  435.32   973.9  439.16
#Mann= 3 , 0 , 0
       0     .12       0  462.25    .045       0  483.09     .12       0
Bank Sta=462.25,483.09
XS Rating Curve= 0 ,0
Exp/Cntr=0.3,0.1

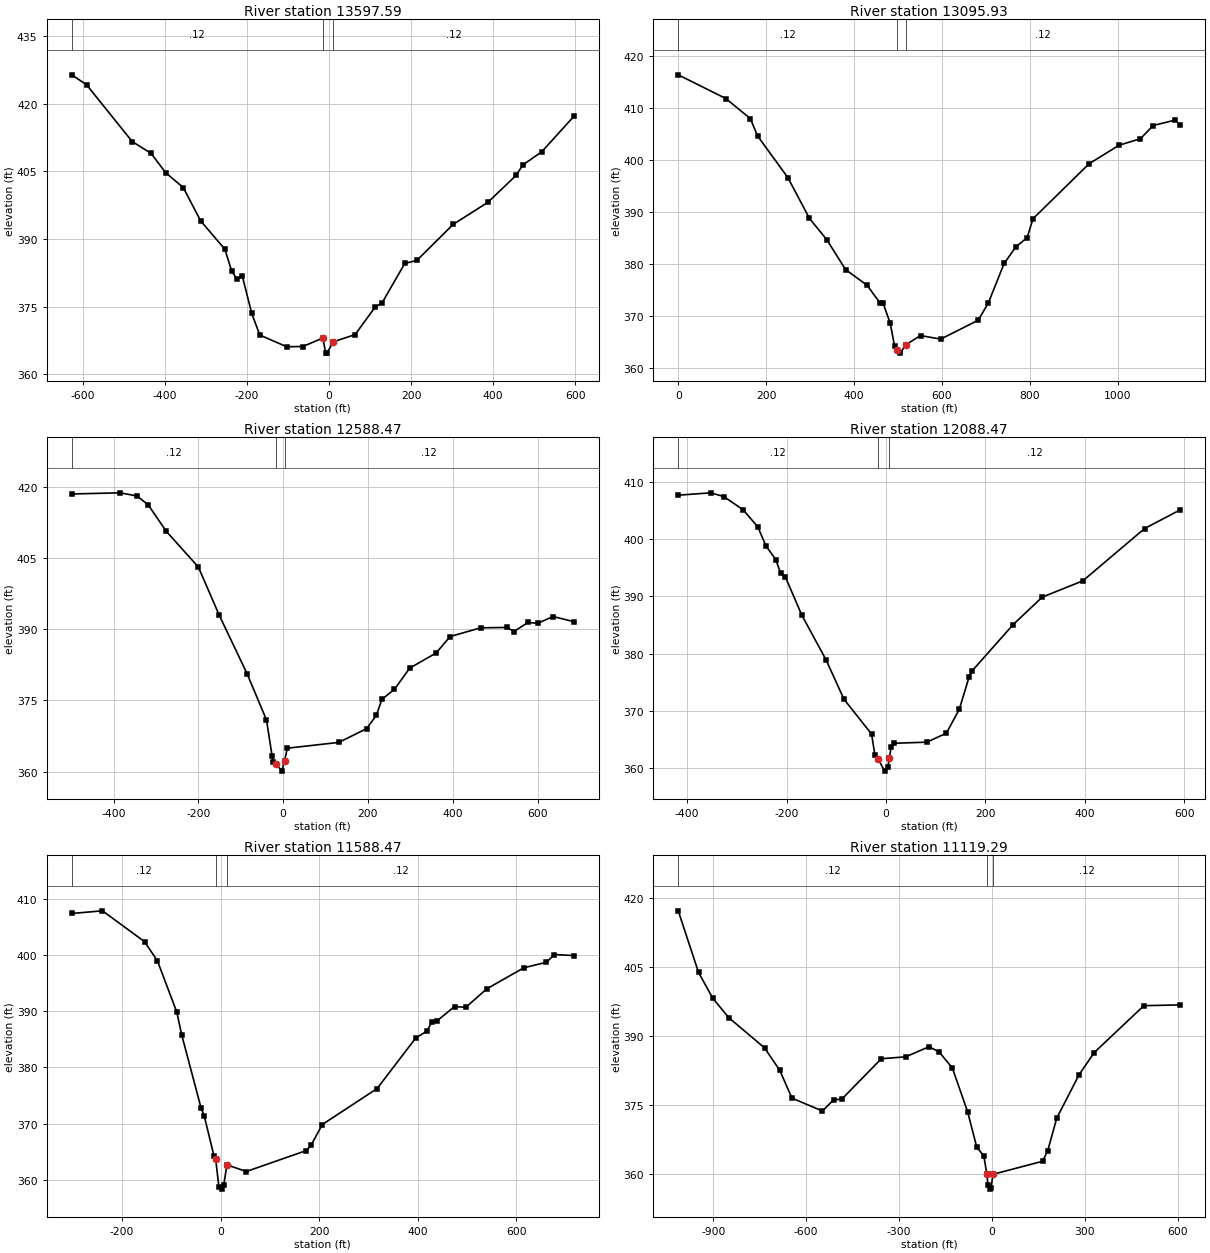
Type RM Length L Ch R = 1 ,13597.59,521.0212,509.1174,491.5662
XS GIS Cut Line= 4
   2455560.63375    332565.64221   2456073.70194    332532.07403
   2456429.72518    332508.78044   2456635.57648    332221.58122
#Sta/Elev= 30
 -627.41  426.45 -591.39  424.25 -480.04  411.64 -434.19  409.02 -398.16   404.7
 -355.59  401.43 -313.02  394.01 -254.07  387.73 -237.69  382.95 -224.59  381.02
 -211.49  381.74 -188.57  373.47 -168.92  368.68 -103.43  366.08  -64.15  366.13
  -15.05  368.01    -8.5  364.79   -5.23  364.66   10.26  367.17   63.51  368.77
  112.61  374.92  128.98  375.77  184.62  384.57  214.08  385.25  302.43  393.23
   387.5  398.16  456.21  404.14  472.56  406.45  518.37  409.34  596.89  417.22
#Mann= 3 , 0 , 0
 -627.41     .12       0  -15.05    .045       0   10.26     .12       0
Bank Sta=-15.05,10.26
XS Rating Curve= 0 ,0
Exp/Cntr=0.3,0.1

Type RM Length L Ch R = 1 ,13095.93,981.4587,1007.46,1016.131
XS GIS Cut Line= 4
2455833.18667795333228.7501327692456273.36886844332967.681757271
2456606.18349153332770.2920601822456849.47204694332766.755649939
#Sta/Elev= 30
       0  416.44  108.26  411.88  164.03  408.01  180.43  404.68  249.33  396.67
  298.54  388.81  337.91  384.72  380.55  378.98  429.76  375.94  459.29   372.5
  465.85  372.55  482.25  368.61  492.09  364.26  497.05  363.45  505.22   362.9
  517.51  364.51  551.13  366.28  597.04   365.6   682.3  369.23  705.25  372.54
  741.32  380.15  767.56   383.3  793.79  385.14  806.91  388.75  934.41  399.32
 1002.54  402.89  1051.2  404.15  1080.4  406.69 1129.06  407.71 1142.04  406.82
#Mann= 3 , 0 , 0
       0     .12       0  497.05    .045       0  517.51     .12       0
Bank Sta=497.05,517.51
XS Rating Curve= 0 ,0
Exp/Cntr=0.3,0.1

Type RM Length L Ch R = 1 ,12588.47,499.4636,499.9999,490.1347
XS GIS Cut Line= 3
   2455900.71115    333526.04416   2456383.34371    333400.92827
   2457047.03464     333229.3935
#Sta/Elev= 30
 -498.59  418.47 -383.78  418.71 -344.42  418.03 -318.18  416.16 -275.53  410.59
 -200.09  403.09 -150.89  392.95  -85.28  380.64  -39.36  370.88  -26.24  363.36
  -22.96  362.05   -16.4  361.59   -3.28   360.1    3.28  362.33    9.84  364.93
   131.2  366.15  196.79  369.05  219.75  371.85  232.87  375.23  262.39  377.32
  298.47   381.8  360.79  384.98  393.59  388.44  465.75  390.28  528.06  390.36
  544.46   389.5  577.26  391.41  600.22  391.23   636.3  392.66   685.5  391.58
#Mann= 3 ,-1 , 0
 -498.59     .12       0   -16.4    .045       0    3.28     .12       0
Bank Sta=-16.4,3.28
XS Rating Curve= 0 ,0
Exp/Cntr=0.3,0.1

Type RM Length L Ch R = 1 ,12088.47,496.2543,500,502.5456
XS GIS Cut Line= 3
   2456199.42676    334021.26823   2456651.27658    333784.83268
   2457094.47254    333552.92534
#Sta/Elev= 30
 -417.86  407.66 -352.48  408.07 -326.33  407.42  -287.1   405.1 -257.68  402.12
 -241.34  398.81 -221.72  396.44 -211.91   394.1 -202.11  393.36 -169.42  386.78
 -120.38  378.93  -84.42  372.08  -28.85     366  -22.31  362.43  -15.77  361.71
   -2.69  359.54    3.84  360.29    7.11  361.86   10.38  363.74   16.92   364.4
    82.3  364.59  121.53  366.15  147.69  370.33   167.3  375.95  173.84  377.06
  255.57  385.06  314.42  389.88  396.15  392.72  520.39  401.84  592.31  405.11
#Mann= 3 , 0 , 0
 -417.86     .12       0  -15.77    .045       0    7.11     .12       0
Bank Sta=-15.77,7.11
XS Rating Curve= 0 ,0
Exp/Cntr=0.3,0.1

Type RM Length L Ch R = 1 ,11588.47,461.0393,469.1768,474.1958
XS GIS Cut Line= 3
   2456450.03813    334401.20481   2456912.82724    334216.66712
   2457395.90501    334024.03922
#Sta/Elev= 30
 -301.88  407.45  -239.6  407.92 -154.37  402.43 -128.15  399.01  -88.82  389.86
  -78.99  385.84  -39.65  372.78   -33.1  371.33  -13.43  364.23   -9.98  363.66
    -3.6  358.78    2.96  358.32    6.24  358.98   12.79  362.65   52.13  361.46
   173.4  365.18  183.24   366.1  206.16  369.83  317.37  376.24  395.87  385.27
  418.77  386.49  428.58  388.17  438.39  388.27  474.37  390.86  497.27  390.72
  539.79  394.01  615.02  397.77  660.81  398.75  677.17  400.13  716.42  399.95
#Mann= 3 , 0 , 0
 -301.88     .12       0   -9.98    .045       0   12.79     .12       0
Bank Sta=-9.98,12.79
XS Rating Curve= 0 ,0
Exp/Cntr=0.3,0.1

Type RM Length L Ch R = 1 ,11119.29,520.8438,530.8229,522.9866
XS GIS Cut Line= 3
   2455920.73243    334888.42135   2456915.93911    334697.75572
   2457517.95496    334610.64369
#Sta/Elev= 30
-1013.31  417.28 -947.72  403.88 -901.81  398.28 -849.34     394 -734.57  387.48
 -685.38  382.59 -646.02  376.55 -547.64  373.75 -511.57   376.2 -485.34   376.3
 -357.44  385.12 -278.74  385.53 -203.32  387.73 -170.52  386.59 -127.89  383.09
   -78.7  373.59  -49.19  365.89  -26.23  363.96   -16.4  359.95  -13.12  357.67
   -6.56  356.76   -3.28  356.93    3.27  359.98  163.52  362.82  179.87  365.08
   209.3  372.21  281.25  381.63  330.31  386.47  490.55  396.65  608.29  396.83
#Mann= 3 , 0 , 0
-1013.31     .12       0   -16.4    .045       0    3.27     .12       0
Bank Sta=-16.4,3.27
XS Rating Curve= 0 ,0
Exp/Cntr=0.3,0.1

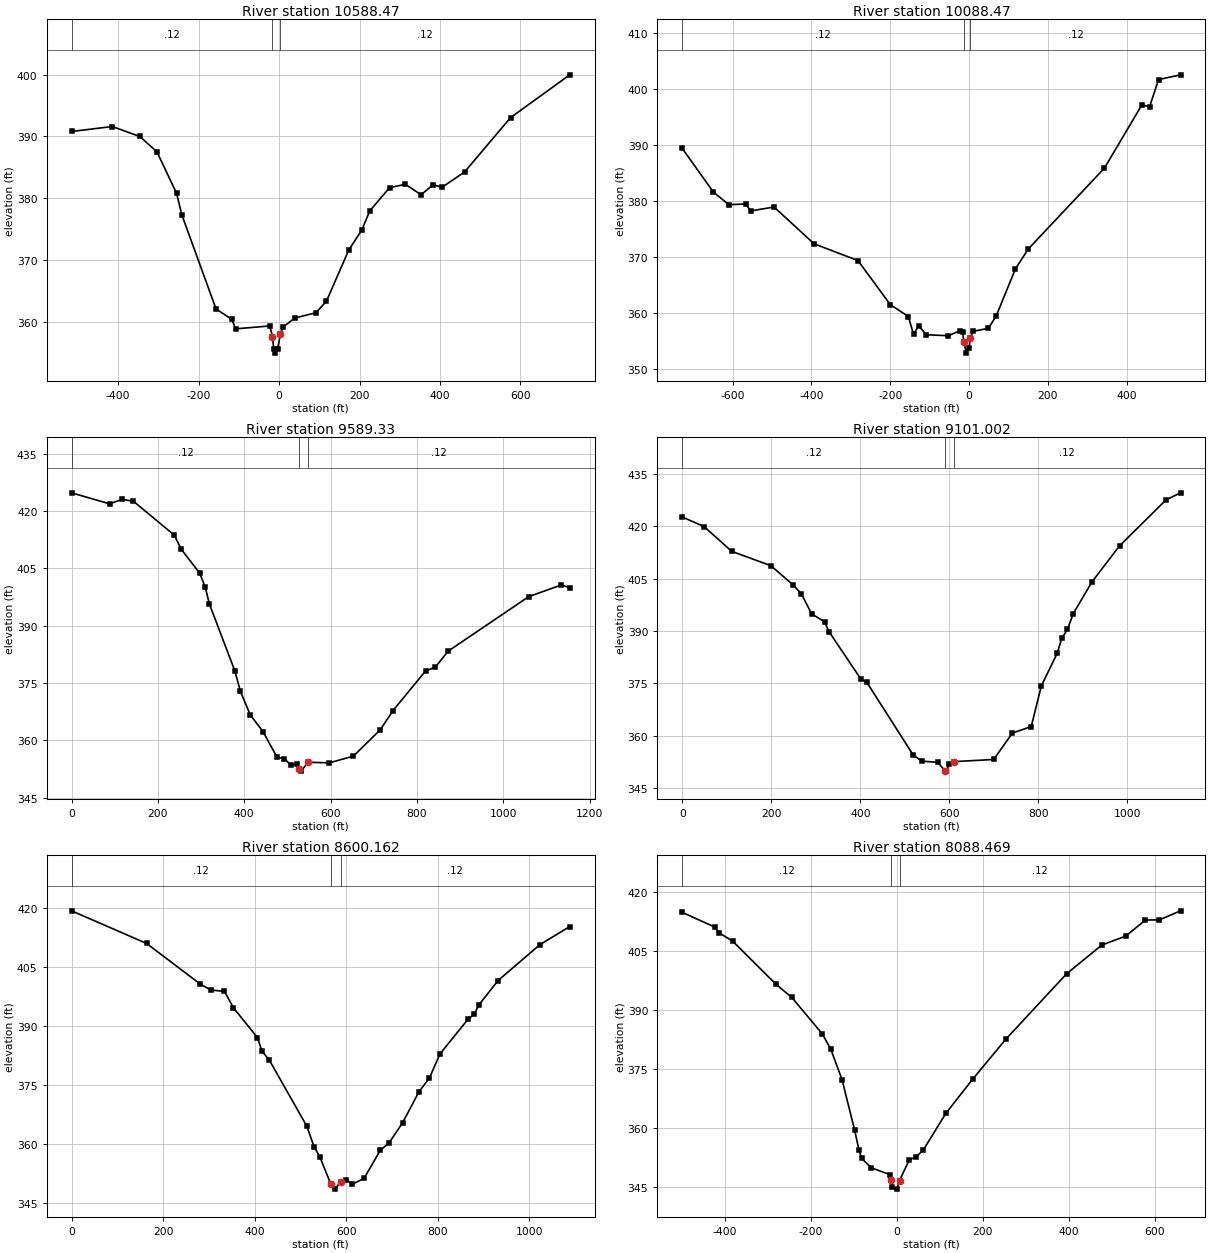
Type RM Length L Ch R = 1 ,10588.47,483.8662,500.0002,512.3649
XS GIS Cut Line= 3
   2456535.97399    335246.17162   2457040.95067    335142.21251
   2457748.85772    334997.36241
#Sta/Elev= 30
 -515.57  390.79 -414.41  391.59 -345.89  389.98 -303.47   387.5 -254.52  380.77
 -241.47  377.28 -156.63  362.08 -117.47  360.38 -107.68  358.85  -22.84  359.32
  -16.32  357.57  -13.05  355.57   -9.79  354.92   -3.26  355.64    3.27  357.98
    9.81  359.15   39.23   360.6   91.55  361.45   117.7  363.31  173.29  371.61
  205.98  374.87   225.6  377.95  274.64   381.7  313.88  382.24  353.11  380.56
  382.54  382.15  405.43  381.78  461.01  384.23  575.44  393.04  722.57  399.96
#Mann= 3 , 0 , 0
 -515.57     .12       0  -16.32    .045       0    3.27     .12       0
Bank Sta=-16.32,3.27
XS Rating Curve= 0 ,0
Exp/Cntr=0.3,0.1

Type RM Length L Ch R = 1 ,10088.47,513.2407,500,484.5606
XS GIS Cut Line= 3
   2456302.85076    335451.52915   2457008.73387    335627.37657
   2457528.11111    335761.42486
#Sta/Elev= 30
 -727.46  389.33 -648.81  381.55 -609.49  379.29 -566.89  379.41 -553.78  378.17
  -494.8  378.87 -393.22   372.3 -281.81   369.3 -199.89  361.44 -154.01  359.31
  -140.9  356.13  -127.8  357.63 -108.14  356.05  -52.43  355.88  -22.94  356.78
  -16.38  356.46  -13.11  354.72   -6.55  352.77       0  353.73    3.27  355.46
    9.81  356.66   49.06   357.2   68.69  359.39  117.75  367.83  150.45  371.39
  343.42  385.82  438.28  397.09   457.9  396.77  480.79  401.63   536.4  402.48
#Mann= 3 , 0 , 0
 -727.46     .12       0  -13.11    .045       0    3.27     .12       0
Bank Sta=-13.11,3.27
XS Rating Curve= 0 ,0
Exp/Cntr=0.3,0.1

Type RM Length L Ch R = 1 ,9589.33 ,1401.094,1473.954,1502.972
XS GIS Cut Line= 4
2456509.30573252336239.2480487672456938.42823386336141.882429853
 2457111.1713267335996.0490601062457556.75704969335796.581283182
#Sta/Elev= 30
       0   424.8   88.01  421.92  117.34  423.09  143.42  422.58  237.94  413.73
  254.24  410.01  296.61  403.79  309.65  400.11  319.43  395.64   378.1  378.23
  391.14  372.84  413.95  366.67  443.31   362.3  476.07  355.56  492.45  355.22
  508.83  353.44  521.94  353.82  527.82  352.46  531.77  351.93  548.06  354.25
   597.3   354.1  652.99  355.86  715.25  362.76  744.74   367.8  820.09  378.15
  843.03  379.18  872.52  383.35 1059.28  397.63 1134.63  400.67 1154.29  399.98
#Mann= 3 , 0 , 0
       0     .12       0  527.82    .045       0  548.06     .12       0
Bank Sta=527.82,548.06
XS Rating Curve= 0 ,0
Exp/Cntr=0.3,0.1

Type RM Length L Ch R = 1 ,9101.002,996.1848,1015.216,1021.92
XS GIS Cut Line= 5
2456510.55737044 336291.157065692456945.37277378336493.445046932
2457068.32823652336494.1031821072457204.05335878336493.445046932
2457543.18096136336666.879083276
#Sta/Elev= 30
       0  422.67   48.94  419.95  110.92  412.84     199  408.72  247.94  403.31
  267.51  400.65  290.35  394.94  319.71  392.61   329.5  389.82  401.27  376.17
  414.32  375.31   518.4  354.48  537.81  352.67   573.4  352.33  590.81  349.85
  592.82   349.8  599.29  351.82  609.31  352.52  699.47  353.14  741.51  360.71
  783.83  362.59  806.62  374.27  842.43  383.66   852.2  387.84  865.22  390.45
  878.24  394.98  920.56  404.14  982.42  414.44  1086.6  427.59 1119.15  429.62
#Mann= 3 , 0 , 0
       0     .12       0  590.81    .045       0  609.31     .12       0
Bank Sta=590.81,609.31
XS Rating Curve= 0 ,0
Exp/Cntr=0.3,0.1

Type RM Length L Ch R = 1 ,8600.162,536.93,511.69,476.84
XS GIS Cut Line= 5
2456297.48266536336411.5282160192456691.57669345336715.683775693
 2456736.7941227336781.7400740242456789.23266611336874.104062527
2457123.63061936337101.726966858
#Sta/Elev= 30
       0  419.28  163.76     411  281.66  400.63  304.58  399.16  334.06  398.82
  353.71  394.64  406.11  387.09  415.94  383.65  432.31  381.31  513.83  364.61
  529.84  359.35  542.64  356.73  566.02  349.97  574.66  348.58  587.94  350.35
   600.4  351.02  613.27  349.82  639.02   351.3  674.42  358.41  693.86  360.36
  723.23  365.42  759.11  373.33  781.95  376.81  804.78   382.9  866.76  391.83
  879.81  392.96   889.6  395.32  932.01  401.58 1023.35  410.69 1088.59  415.29
#Mann= 3 , 0 , 0
       0     .12       0  566.02    .045       0  587.94     .12       0
Bank Sta=566.02,587.94
XS Rating Curve= 0 ,0
Exp/Cntr=0.3,0.1

Type RM Length L Ch R = 1 ,8088.469,512.9053,499.9999,482.1624
XS GIS Cut Line= 3
    2455986.0161    337170.33083   2456484.44653    337188.93414
   2457144.25689     337213.5604
#Sta/Elev= 30
 -498.78  414.81  -423.8  411.09 -414.02  409.66 -381.42  407.47 -280.36  396.45
  -244.5  393.21 -172.78  383.85 -153.22  379.94 -127.14  372.24   -97.8  359.35
  -88.02  354.45   -81.5  352.18  -58.68  349.78   -16.3  348.09  -13.04  346.77
   -9.78  344.87       0  344.37    6.54  346.56   29.42  351.83   45.76  352.63
    62.1  354.37   114.4  363.66  176.51  372.32  254.96  382.66  395.51   399.2
  477.22   406.5  532.79  408.76  578.55  412.85  611.24   412.9  660.27   415.2
#Mann= 3 , 0 , 0
 -498.78     .12       0  -13.04    .045       0    6.54     .12       0
Bank Sta=-13.04,6.54
XS Rating Curve= 0 ,0
Exp/Cntr=0.3,0.1

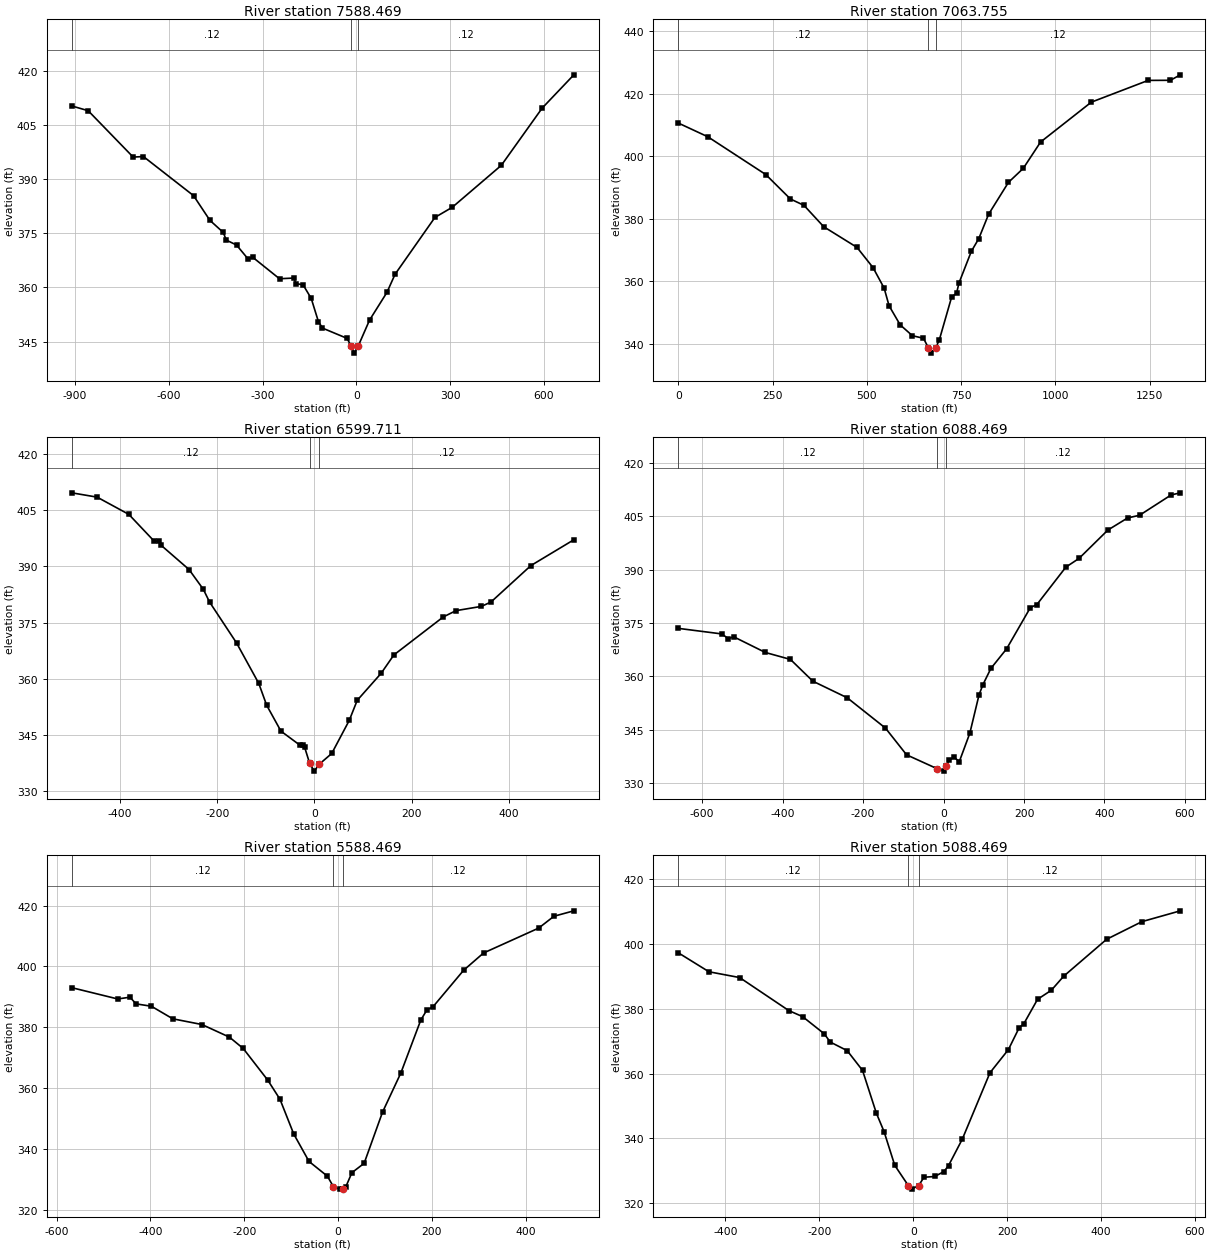
Type RM Length L Ch R = 1 ,7588.469,977.0941,988.7577,993.7749
XS GIS Cut Line= 3
   2455825.31596      338044.897   2456635.83993    337630.28923
   2457253.70123    337309.21999
#Sta/Elev= 30
 -910.41  410.23 -858.01  408.92 -713.92  396.07 -681.17  396.23  -520.7   385.4
 -468.31  378.56 -425.73  375.22 -415.91  373.09 -383.16  371.73 -347.14  367.97
 -330.76   368.3 -245.61  362.39 -199.77  362.59 -193.22  361.04 -170.29  360.73
 -144.09  356.94 -121.17  350.54 -108.07  348.73  -29.47  345.89  -16.37  343.77
   -6.55   341.8    6.54  343.82    42.5  350.94   98.07   358.6  124.22  363.64
  251.72  379.37  307.29  382.18   464.2  393.79  594.96  409.64   696.3  418.85
#Mann= 3 , 0 , 0
 -910.41     .12       0  -16.37    .045       0    6.54     .12       0
Bank Sta=-16.37,6.54
XS Rating Curve= 0 ,0
Exp/Cntr=0.3,0.1

Type RM Length L Ch R = 1 ,7063.755,465.86,464.04,459.51
XS GIS Cut Line= 5
2456482.71293794338216.0800531062456923.22813302337845.827184692
2457020.52649486337838.034221277 2457098.2281111337832.285545111
2457520.62851302337434.220068276
#Sta/Elev= 30
       0  410.66   78.47  406.26  232.14  394.18  297.53  386.36   333.5  384.32
  385.81  377.49  474.09  370.88   516.6  364.41  546.02  357.85   559.1  352.21
  588.46  346.12     621  342.63  650.28  341.83  663.05  338.84   669.8  337.07
  683.01   338.8  692.54   341.4     725  355.02  737.99  356.21  744.48   359.5
  777.21  369.62  796.88  373.67  823.11   381.5  875.58  391.67  914.93  396.16
  960.84  404.58 1095.29  417.32 1246.12  424.29 1305.15  424.32 1331.38  426.07
#Mann= 3 , 0 , 0
       0     .12       0  663.05    .045       0  683.01     .12       0
Bank Sta=663.05,683.01
XS Rating Curve= 0 ,0
Exp/Cntr=0.3,0.1

Type RM Length L Ch R = 1 ,6599.711,526.8891,511.2423,494.5436
XS GIS Cut Line= 3
   2456512.30605    338389.68338   2457001.91564     338292.2925
   2457526.26334    338187.99153
#Sta/Elev= 30
 -499.68  409.65 -447.48   408.5 -382.22   403.9 -330.02  396.75 -320.23  396.74
 -316.97  395.79 -258.24  389.18 -228.87  383.91 -215.82  380.47 -160.35  369.57
 -114.68  358.79  -98.36  352.94     -69  346.04  -29.84  342.28  -23.32  342.32
  -20.06  341.69   -9.96  337.47    -.48  335.36   10.07  337.22    35.6  340.07
   71.68   348.9   88.08  354.26  137.28  361.46  163.51  366.37  265.19  376.51
  291.43   378.2  343.91  379.34  363.59  380.51  445.58  390.22  534.14  397.12
#Mann= 3 ,-1 , 0
 -499.68     .12       0   -9.96    .045       0   10.07     .12       0
Bank Sta=-9.96,10.07
XS Rating Curve= 0 ,0
Exp/Cntr=0.3,0.1

Type RM Length L Ch R = 1 ,6088.469,498.3737,500,496.3019
XS GIS Cut Line= 3
   2456820.28116    339116.77215   2457308.30807    338673.49318
   2457747.36461    338281.70263
#Sta/Elev= 30
 -659.29  373.48 -551.05  371.91 -534.65  370.58 -521.53  371.11 -442.81  366.69
 -380.49  364.74 -324.73  358.61 -239.44  353.95 -144.32  345.41  -91.84  337.89
   -16.4  334.01       0   333.3    6.54  334.63   13.08   336.3   26.15  337.22
   39.23  335.98   65.38  343.98   88.27  354.78   98.07  357.67  117.69   362.2
  156.92  367.74  215.76  379.31  232.11  380.19  304.03  390.71  336.72  393.16
  408.64  401.16  457.68  404.56   487.1   405.3  565.56  411.02  588.45  411.62
#Mann= 3 , 0 , 0
 -659.29     .12       0   -16.4    .045       0    6.54     .12       0
Bank Sta=-16.4,6.54
XS Rating Curve= 0 ,0
Exp/Cntr=0.3,0.1

Type RM Length L Ch R = 1 ,5588.469,502.1185,499.9999,495.3267
XS GIS Cut Line= 3
   2457316.79657     339257.1905   2457734.46667    338872.58366
   2458104.13489    338532.17883
#Sta/Elev= 30
 -567.78  393.02 -469.88  389.31 -443.78  389.89 -430.73   387.7  -398.1  386.92
 -352.41  382.79 -290.41  380.92 -231.68  376.77 -202.31  373.05  -150.1  362.67
    -124  356.39  -94.63  344.97     -62  335.94  -22.84   331.1  -10.19   327.7
    3.26  326.85   10.18  326.89   16.32  327.57   29.37  332.25   55.47  335.33
   94.63  352.12  133.79  365.02  176.21  382.37  189.26   385.7  202.31  386.75
  267.58  398.74     310  404.41  427.47  412.58   460.1  416.48  502.52  418.26
#Mann= 3 ,-1 , 0
 -567.78     .12       0  -10.19    .045       0   10.18     .12       0
Bank Sta=-10.19,10.18
XS Rating Curve= 0 ,0
Exp/Cntr=0.3,0.1

Type RM Length L Ch R = 1 ,5088.469,348.2568,345.5603,335.5764
XS GIS Cut Line= 3
   2457547.72721    339700.66206    2457875.7095    339322.92987
   2458248.51715    338893.57345
#Sta/Elev= 30
 -500.25  397.35 -434.86  391.48 -369.47  389.69 -264.84  379.49 -235.41  377.62
 -189.64  372.35 -176.56  369.77 -140.59  367.12  -107.9  361.02  -78.47  347.81
  -62.12  342.13  -39.24  331.68  -10.17  325.39   -3.27  324.35   11.75  325.47
   22.88  328.02   45.75  328.25   65.36  329.77   75.16  331.61  104.57  339.81
   163.4  360.29  202.61  367.44  225.49  374.18  235.29  375.38   264.7  382.97
  294.12  385.78  320.26   390.1  411.76  401.51  486.92  406.96  568.62   410.3
#Mann= 3 ,-1 , 0
 -500.25     .12       0  -10.17    .045       0   11.75     .12       0
Bank Sta=-10.17,11.75
XS Rating Curve= 0 ,0
Exp/Cntr=0.3,0.1

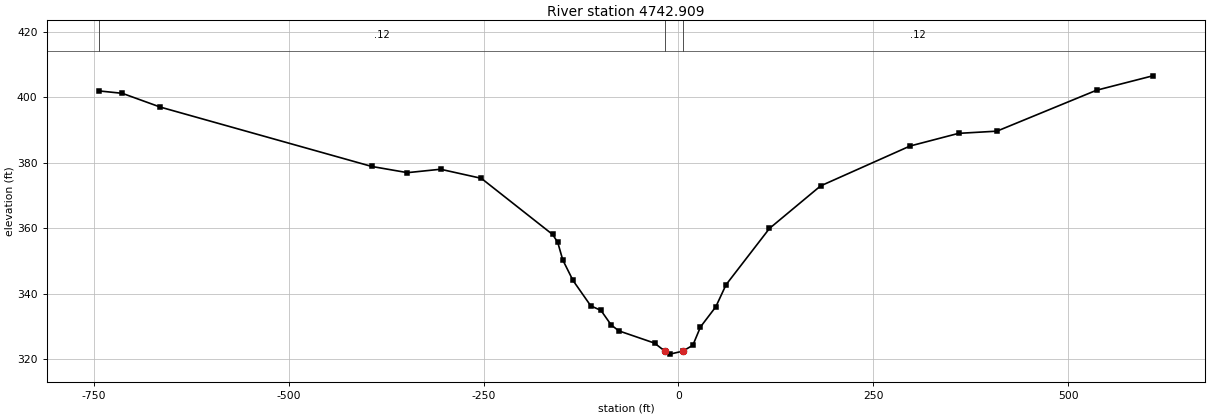
Type RM Length L Ch R = 1 ,4742.909,672.973,654.4398,624.5975
XS GIS Cut Line= 3
   2457690.02253    340078.32469   2458129.42815    339547.27391
    2458465.8471    338976.97912
#Sta/Elev= 30
 -742.85  401.93 -713.45  401.21 -664.45  396.99 -393.32  378.87 -347.58  376.98
 -305.12  378.02 -252.85  375.25 -161.38   358.1 -154.85  355.75 -148.32  350.32
 -135.25  344.08 -112.38   336.3  -99.32  334.91  -86.25  330.48  -76.45  328.67
  -30.64  324.93  -17.53  322.51  -10.97  321.56    5.42  322.45   18.53  324.26
   28.36  329.87   48.03  336.02   61.14  342.75  116.87  359.95  182.42  372.93
  297.15  385.11  359.43  388.98   408.6  389.65  536.43  402.15  608.55  406.55
#Mann= 3 , 0 , 0
 -742.85     .12       0  -17.53    .045       0    5.42     .12       0
Bank Sta=-17.53,5.42
XS Rating Curve= 0 ,0
Exp/Cntr=0.3,0.1