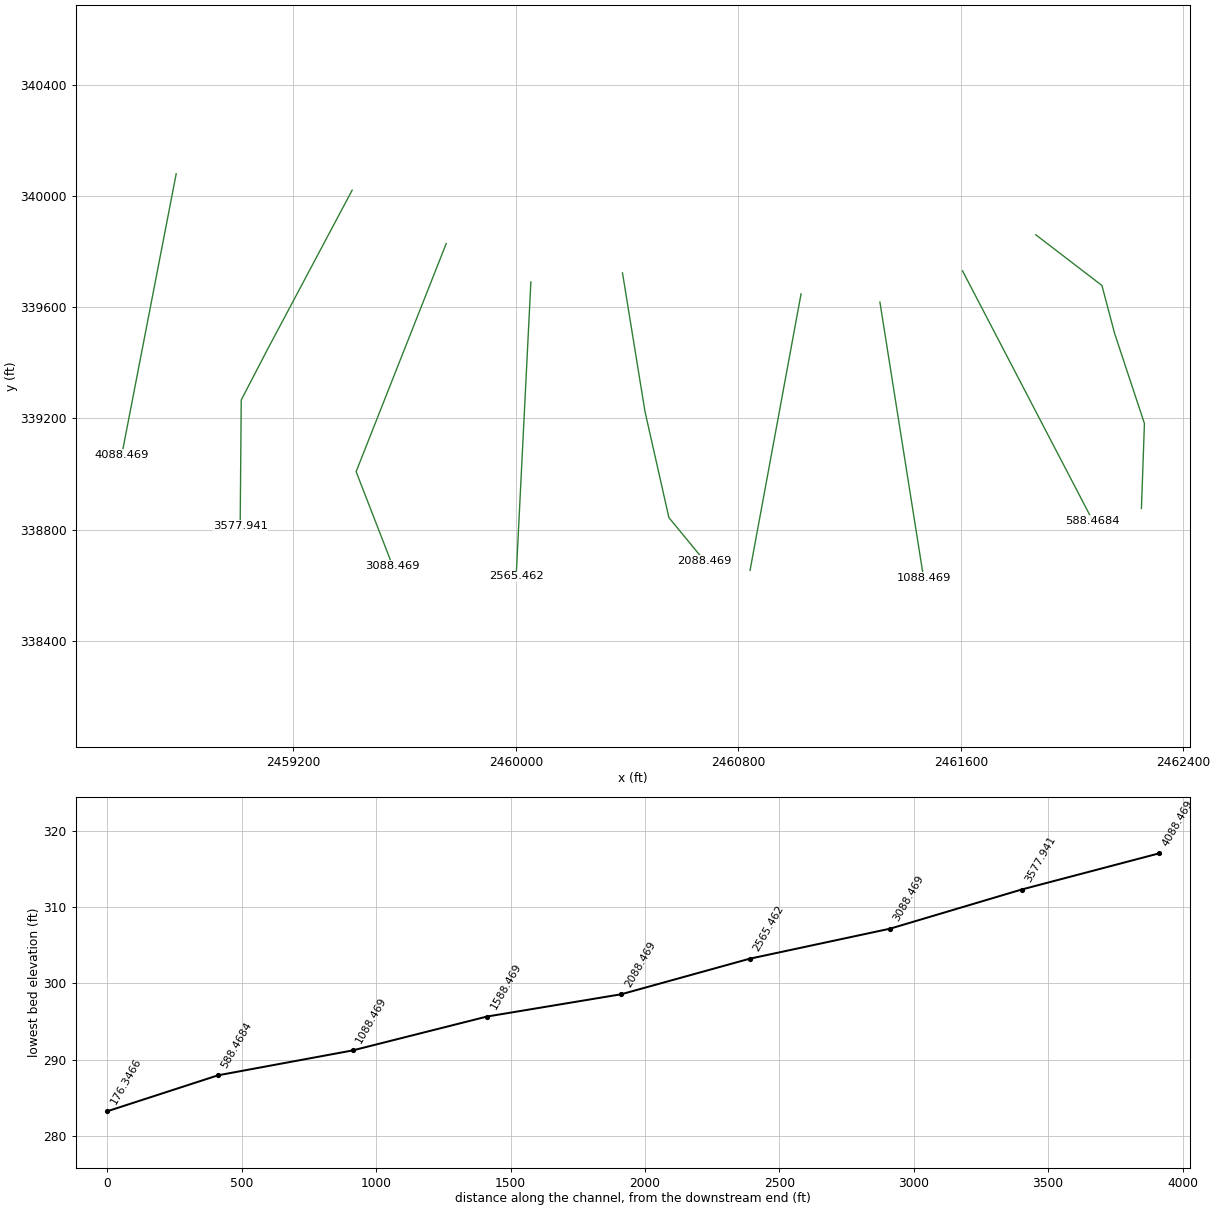
HEC-RAS study RattlesnakeRun.prj: Basic Project File

--- RattlesnakeRun.g01 (geometry) --- (continued)

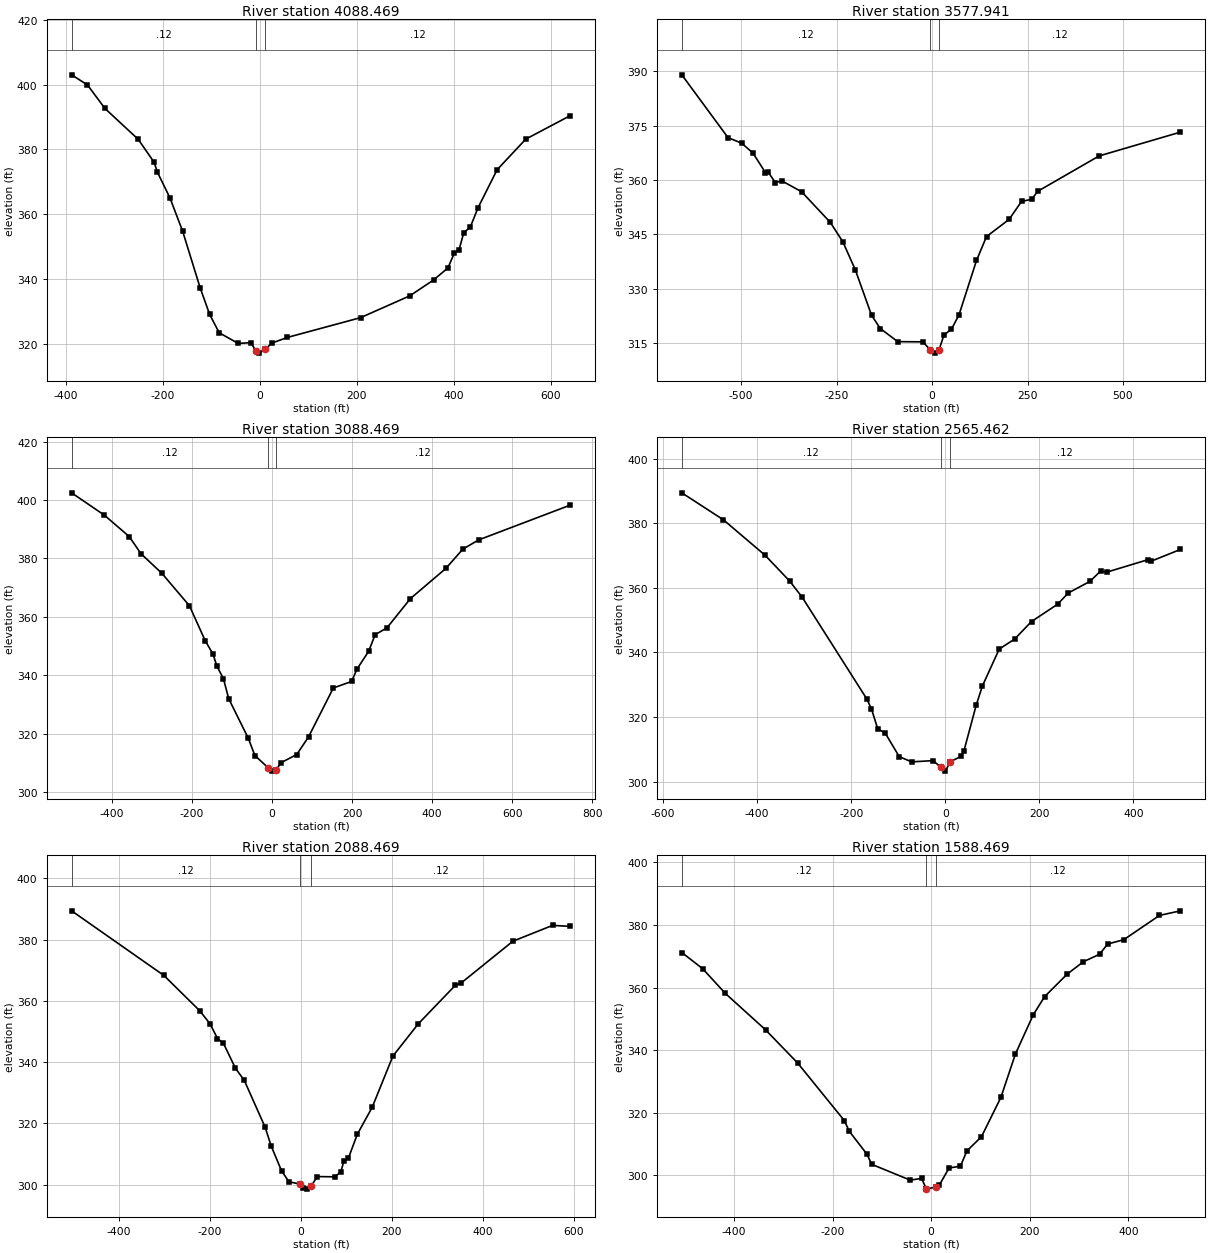
Type RM Length L Ch R = 1 ,4088.469,518.472,510.528,499.8195
XS GIS Cut Line= 3
   2458778.63715    340079.57829   2458683.42113     339587.7653
   2458583.11491    339069.65971
#Sta/Elev= 30
 -387.95  403.08 -355.21  399.96  -319.2  392.69 -250.44  383.13  -217.7  376.04
 -211.15  373.06 -184.96  365.01 -158.76  354.69 -122.75  337.24  -103.1     329
  -83.46  323.35  -44.17  320.05  -17.98  320.31    -8.4  317.85    -1.6  317.06
   11.66  318.22   24.59  320.14   57.33  321.92  208.05  328.02  309.66  334.76
  358.83  339.68  388.33  343.38  401.44  347.93  411.27  348.98   421.1  354.32
  434.22  355.91   450.6  362.03  489.94  373.77  548.94   383.2  640.72  390.47
#Mann= 3 ,-1 , 0
 -387.95     .12       0    -8.4    .045       0   11.66     .12       0
Bank Sta=-8.4,11.66
XS Rating Curve= 0 ,0
Exp/Cntr=0.3,0.1

Type RM Length L Ch R = 1 ,3577.941,483.7851,489.4719,489.4829
XS GIS Cut Line= 4
   2459411.46299    340020.81562   2459103.14503     339440.8486
   2459012.55926    339266.36667   2459008.68525    338814.21862
#Sta/Elev= 30
 -655.06  388.98 -534.15  371.68  -498.2  370.14 -468.79  367.43 -436.11  362.04
 -429.58  362.27 -409.97  359.27 -393.63   359.8 -341.35  356.76 -266.19  348.32
 -233.51  342.99 -200.83  335.26 -158.35  322.76 -135.48   319.1  -89.73  315.48
  -24.37  315.43   -4.77  313.28    8.32  312.32   18.15  313.16   31.26  317.31
   50.92  318.91   70.58  322.84  116.45  337.84  142.66  344.43  201.64  349.14
  234.41  354.11  260.62  354.68     277  356.91  437.55  366.64  650.53   373.2
#Mann= 3 , 0 , 0
 -655.06     .12       0   -4.77    .045       0   18.15     .12       0
Bank Sta=-4.77,18.15
XS Rating Curve= 0 ,0
Exp/Cntr=0.3,0.1

Type RM Length L Ch R = 1 ,3088.469,511.7346,523.0071,531.6415
XS GIS Cut Line= 4
   2459749.60568    339828.60472   2459565.92232    339363.59712
   2459425.66998    339008.53746   2459556.86263    338670.12147
#Sta/Elev= 30
 -499.97  402.49 -418.28  394.85 -356.19  387.52 -326.78  381.64 -274.49   374.9
 -205.87  363.82 -166.66   351.9 -147.05  347.25 -137.25  343.15 -120.91  338.79
 -107.84     332  -58.82   318.4  -42.48  312.52   -9.52  308.35       0  307.18
   10.46  307.56   22.84  310.08   61.99  312.86   91.36  318.89  153.36  335.66
  199.04   337.9  212.09  342.05  241.45  348.21  257.77  353.92  287.13  356.24
  345.86  366.28  434.07  376.58  476.58   383.2  515.82  386.35  744.71  398.28
#Mann= 3 ,-1 , 0
 -499.97     .12       0   -9.52    .045       0   10.46     .12       0
Bank Sta=-9.52,10.46
XS Rating Curve= 0 ,0
Exp/Cntr=0.3,0.1

Type RM Length L Ch R = 1 ,2565.462,468.7413,476.993,482.5458
XS GIS Cut Line= 3
   2460054.05914    339690.57907   2460026.08741    339130.73406
   2460001.15603    338631.74556
#Sta/Elev= 30
  -560.1  389.43 -471.59  381.06 -383.09  370.09 -330.64  362.07 -304.41  357.12
 -166.74  325.56  -156.9  322.49 -143.79  316.41  -127.4  314.94   -97.9  307.72
  -71.67   306.1  -25.78  306.48  -10.01  304.49     .44  303.23      10  306.09
    33.1  307.78   39.63  309.48   65.75  323.66   78.81  329.58  114.73  341.05
  147.39  344.12  183.31  349.57  238.82  354.92  261.68  358.43  307.39  361.98
  330.25  365.19  343.31  364.86  431.48  368.75  438.01  368.27  500.05   371.9
#Mann= 3 ,-1 , 0
  -560.1     .12       0  -10.01    .045       0      10     .12       0
Bank Sta=-10.01,10
XS Rating Curve= 0 ,0
Exp/Cntr=0.3,0.1

Type RM Length L Ch R = 1 ,2088.469,508.9979,500.0003,485.0293
XS GIS Cut Line= 4
   2460383.45842    339723.35066   2460464.22925    339225.54227
   2460550.35211    338843.29829   2460677.95619    338688.35043
#Sta/Elev= 30
 -504.32  389.37 -301.28  368.28 -222.69   356.8 -199.76   352.5 -183.39  347.71
 -170.29  346.14 -144.09  338.05 -124.44  334.03   -78.6  318.77   -65.5  312.72
  -42.57  304.56   -26.2  300.95   -2.77  300.27    4.18  298.79   13.23  298.57
   22.37  299.45   35.92  302.67    75.1  302.58   88.16   304.3   94.69  307.78
  104.49  308.64  124.08  316.44  156.73  325.22  202.44  341.98  257.95  352.45
  339.58  365.04  352.64  365.83  466.29  379.45   553.7  384.62  592.55   384.3
#Mann= 3 , 0 , 0
 -504.32     .12       0   -2.77    .045       0   22.37     .12       0
Bank Sta=-2.77,22.37
XS Rating Curve= 0 ,0
Exp/Cntr=0.3,0.1

Type RM Length L Ch R = 1 ,1588.469,486.3982,499.9999,503.1459
XS GIS Cut Line= 3
   2461025.67072    339647.94727   2460934.50095    339153.80816
   2460842.24851    338653.80227
#Sta/Elev= 30
 -505.46  371.21 -463.05  366.01 -417.37  358.16 -335.79  346.52 -270.54  335.89
 -175.91  317.51 -166.13  314.15 -130.23  306.81 -120.45  303.55  -42.14   298.5
   -19.3  299.09   -9.99  295.73   -9.51  295.64   10.07  296.36    16.7  296.97
   36.38   302.4   59.34  302.96   72.46  307.85  101.99  312.38  141.35  324.93
  170.87  338.81  206.96  351.31  229.92   357.1  275.84  364.32  308.64  368.27
  341.45  370.65  357.85  373.92  390.65  375.31  462.82  383.05  505.46  384.52
#Mann= 3 ,-1 , 0
 -505.46     .12       0   -9.99    .045       0   10.07     .12       0
Bank Sta=-9.99,10.07
XS Rating Curve= 0 ,0
Exp/Cntr=0.3,0.1

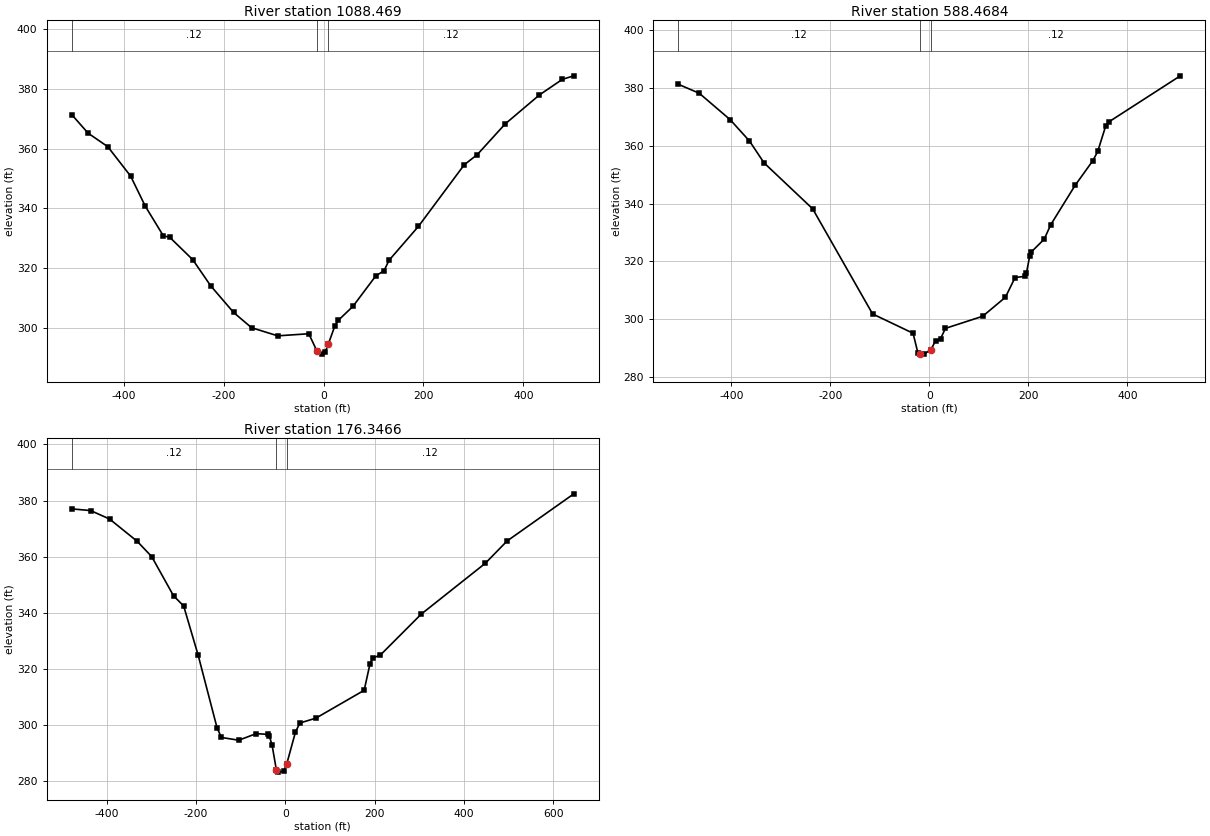
Type RM Length L Ch R = 1 ,1088.469,489.3726,500.0005,508.6507
XS GIS Cut Line= 3
    2461309.1567     339618.3804   2461387.93771     339121.0369
   2461466.28335    338626.44078
#Sta/Elev= 30
 -503.54  371.45 -470.85  365.24 -431.61  360.73 -385.83  350.86  -356.4  340.74
 -320.44  330.86 -307.36  330.31 -261.58  322.85 -225.61  314.08 -179.84  305.15
 -143.87  300.04  -91.55  297.32  -29.43  298.02  -13.08  292.21   -3.27  291.19
    3.27  291.82    9.82  294.66   22.91  300.73   29.46   302.5   58.91   307.2
  104.73  317.44   121.1  319.13  130.92   322.6  189.83  333.99  281.47  354.64
  307.66  358.07   363.3  368.32  432.03  378.07  477.85  383.29  500.76  384.46
#Mann= 3 , 0 , 0
 -503.54     .12       0  -13.08    .045       0    9.82     .12       0
Bank Sta=-13.08,9.82
XS Rating Curve= 0 ,0
Exp/Cntr=0.3,0.1

Type RM Length L Ch R = 1 ,588.4684,419.0839,412.1219,405.7667
XS GIS Cut Line= 3
   2461606.14823    339730.77059   2461837.42992     339286.9306
   2462074.80444    338831.39805
#Sta/Elev= 30
 -507.08  381.35 -464.55  378.22  -402.4  369.12 -363.15  361.69 -333.71  354.12
 -235.57  338.23 -114.54  301.85  -32.76  295.16  -22.95  288.34  -19.68  288.14
  -10.63  287.93    3.22  289.46   13.04  292.63   22.85  293.29   32.67  296.85
  107.92  301.04  153.73   307.6  173.36  314.45  192.99  314.84  196.26  315.99
   202.8  321.83  206.07  323.29  232.25  327.74  245.33  332.71  294.41   346.3
   330.4   354.9  340.22  358.07  356.58  367.02  363.12  368.36  507.08  384.26
#Mann= 3 , 0 , 0
 -507.08     .12       0  -19.68    .045       0    3.22     .12       0
Bank Sta=-19.68,3.22
XS Rating Curve= 0 ,0
Exp/Cntr=0.3,0.1

Type RM Length L Ch R = 1 ,176.3466,177.2896,176.3466,183.1725
XS GIS Cut Line= 5
   2461869.79665    339860.22539   2462107.52059    339677.96492
   2462153.20488    339505.42492    2462260.3792    339181.66244
   2462249.57083    338876.06758
#Sta/Elev= 30
 -478.32  377.04 -435.99  376.44 -393.66  373.43  -331.8   365.5 -299.24  360.03
  -250.4  346.09 -227.61  342.43 -195.05  324.82 -152.81  298.99 -143.07  295.57
 -104.13  294.58  -65.19  296.93  -39.22  296.67  -35.98  296.24  -29.49  292.79
  -19.75  283.83  -16.51  283.21   -3.53  283.55       3  285.96   22.67  297.39
   32.51   300.7   68.58  302.45   176.8  312.38  189.91  321.88  196.47  323.89
  212.87  324.91  304.69  339.54  448.11  357.64  496.91  365.59  646.54  382.41
#Mann= 3 , 0 , 0
 -478.32     .12       0  -19.75    .045       0       3     .12       0
Bank Sta=-19.75,3
XS Rating Curve= 0 ,0
Exp/Cntr=0.3,0.1

Chan Stop Cuts=-1
Use User Specified Reach Order=0
Composite Channel Slope=5